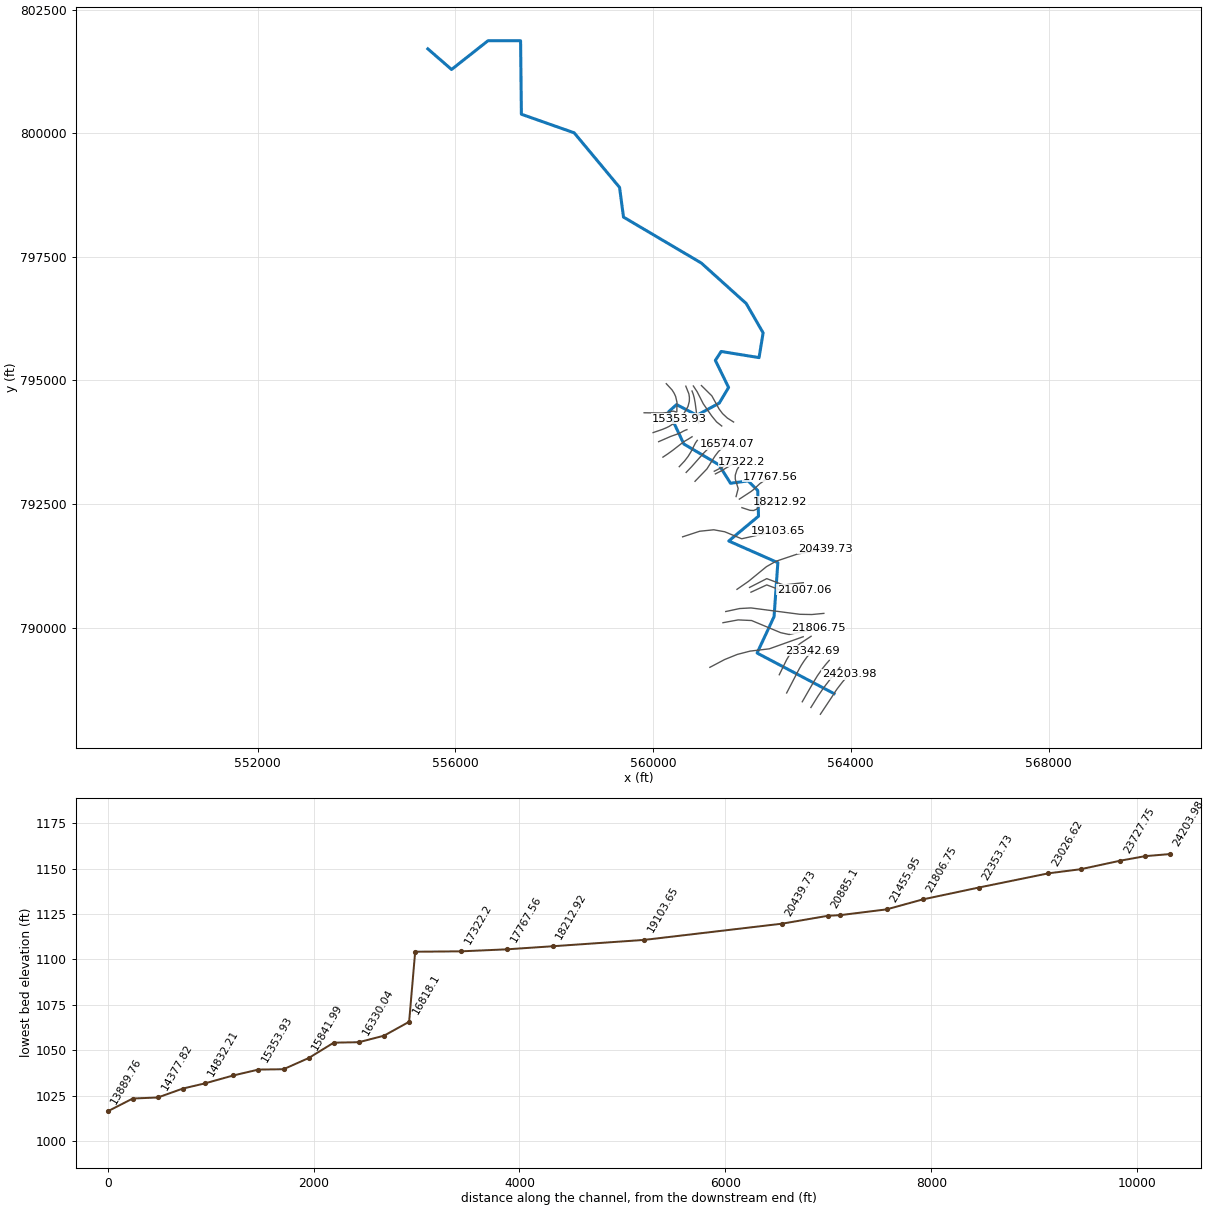
--- 10956_ras.prj (project) ---

Proj Title=10956
Current Plan=p01
Default Exp/Contr=0.3,0.1
English Units
Geom File=g01
Flow File=f01
Plan File=p01
Y Axis Title=Elevation
X Axis Title(PF)=Main Channel Distance
X Axis Title(XS)=Station
BEGIN DESCRIPTION:
RFD model 10956 exported to HEC-RAS
END DESCRIPTION:

--- 10956_ras.p01 (plan) ---

Plan Title=Plan 01
Program Version=4.10
Short Identifier=Plan 01
Geom File=g01
Flow File=f01
Subcritical Flow
Calc Critical at every XS
Secant Critical Depth

--- 10956_ras.f01 (steady flow) ---

Flow Title=Flow 01
Program Version=5.01
Number of Profiles= 6
Profile Names=10yr,25yr,50yr,100yr,100plus,500yr
River Rch & RM=10956,77,24203.98
 4030.72 6459.76 8754.0710811.23 15784.417399.05
River Rch & RM=10956,77,23965.86
 4032.69 6463.02 8758.5910816.92 15792.717407.28
River Rch & RM=10956,77,23727.75
  4054.4 6499.07  8808.610879.8815884.6317498.52
River Rch & RM=10956,77,23342.69
 4139.41  6639.2 9002.1211122.6216239.0317846.14
River Rch & RM=10956,77,23026.62
 4144.84 6648.23 9014.6511138.4116262.0817868.95
River Rch & RM=10956,77,22353.73
 4953.86 7957.6410802.2613357.1319501.42 20916.2
River Rch & RM=10956,77,21806.75
 4967.47 7980.27 10833.713396.7719559.2820972.05
River Rch & RM=10956,77,21455.95
 4972.68 7988.9410845.7513411.9619581.4620993.46
River Rch & RM=10956,77,21007.06
 5545.84  8936.112156.1915057.81 21984.423272.12
River Rch & RM=10956,77, 20885.1
 5546.38    893712157.4415059.3921986.7123274.32
River Rch & RM=10956,77,20439.73
 5561.12 8961.5912191.6815102.6322049.8423334.48
River Rch & RM=10956,77,19103.65
 5792.12 9346.2112726.3715776.9923034.4124266.65
River Rch & RM=10956,77,18212.92
 5813.09  9381.312775.31 15838.923124.7924352.53
River Rch & RM=10956,77,17767.56
 5834.14 9416.4812824.3415900.8723215.2724438.29
River Rch & RM=10956,77, 17322.2
 5840.48  9427.112839.1415919.5823242.5924464.21
River Rch & RM=10956,77,16876.86
 5848.05 9439.75 12856.815941.91 23275.224495.15
River Rch & RM=10956,77, 16818.1
 5852.63 9447.4212867.4815955.4223294.9224513.86
River Rch & RM=10956,77,16574.07
 5854.38 9450.3512871.58 15960.623302.4824521.05
River Rch & RM=10956,77,16330.04
 5856.82 9454.4412877.2915967.8523313.0624531.12
River Rch & RM=10956,77,16086.01
 5884.07 9500.1312941.0916048.6123430.97 24643.2
River Rch & RM=10956,77,15841.99
 5886.86 9504.8112947.6216056.8823443.0524654.68
River Rch & RM=10956,77,15597.96
 5894.51 9517.6612965.5716079.6123476.2424686.25
River Rch & RM=10956,77,15353.93
 5895.56 9519.4112968.0116082.7123480.7624690.55
River Rch & RM=10956,77, 15109.9
 5906.12 9537.1512992.8216114.1623526.6824734.29
River Rch & RM=10956,77,14832.21
 5919.78 9560.1113024.9316154.86 23586.124790.89
River Rch & RM=10956,77,14621.84
 5946.09  9604.313086.7116233.1623700.4124899.65
River Rch & RM=10956,77,14377.82
 5947.65 9606.9213090.3716237.7923707.1824906.08
River Rch & RM=10956,77,14133.79
 5950.95 9612.46 13098.116247.5923721.4824919.66
River Rch & RM=10956,77,13889.76
  5975.7 9653.85 13155.816320.55   2382825020.35
River Rch & RM=10956,77,13749.76
 5976.74 9655.5913158.2516323.6423832.5225024.63
River Rch & RM=10956,77,13645.73
 5978.84 9659.1213163.1516329.8523841.5825033.19
River Rch & RM=10956,77, 13401.7
 6003.18 9699.7513219.7516401.3423945.9525131.56
River Rch & RM=10956,77,13157.68
 6004.57 9702.0913223.0116405.4723951.9825137.26
River Rch & RM=10956,77,12913.65
 6008.23 9708.2213231.5716416.2923967.7925152.21
River Rch & RM=10956,77,12669.62
 6021.22 9730.0113262.0116454.8624024.09 25205.6
River Rch & RM=10956,77,12425.59
 6023.84 9734.3913268.1216462.5924035.3825216.27
River Rch & RM=10956,77,12181.56
 6027.86 9741.1213277.5116474.4624052.7225232.63
River Rch & RM=10956,77,11937.53
 6029.44 9743.7613281.1916479.1124059.5125239.03
River Rch & RM=10956,77,11693.51
 6033.82 9751.08 13291.416492.0224078.35 25256.8
River Rch & RM=10956,77,11449.48
 6061.29 9796.8513355.0716572.3724195.65 25366.9
River Rch & RM=10956,77,11205.45
 6062.16 9798.3213357.1116574.9424199.4225370.45
River Rch & RM=10956,77,11107.82
 6105.04 9869.4913455.8916699.3324381.0225539.83
River Rch & RM=10956,77,10961.42
 6106.26 9871.5413458.7416702.9324386.2825544.79
River Rch & RM=10956,77,10811.09
 6250.0810109.1713787.5717115.9224989.2426102.23
River Rch & RM=10956,77,10717.39
 6251.1310110.91   1379017118.9924993.7226106.44
River Rch & RM=10956,77,10473.37
    625210112.3713792.0317121.5524997.4726109.95
River Rch & RM=10956,77,10187.49
 6257.0610120.82 13803.817136.4325019.18 26130.3
River Rch & RM=10956,77,10091.86
 6259.6610125.1713809.8817144.11 25030.426140.82
River Rch & RM=10956,77,9962.987
 6261.2310127.7913813.5317148.7225037.1426147.13
River Rch & RM=10956,77,9895.886
 6266.3910136.4513825.6117164.0325059.4826168.17
River Rch & RM=10956,77,9764.576
 6268.6410140.2113830.8717170.6725069.1826177.28
River Rch & RM=10956,77,9474.158
  6278.910157.3613854.7717200.89 25113.326218.62
River Rch & RM=10956,77, 9230.13
 6288.1510172.8913876.4717228.3825153.4426256.44
River Rch & RM=10956,77,8986.102
 6301.4310195.1313907.5117267.6725210.7926310.33
River Rch & RM=10956,77,8742.074
 6305.3810201.7613916.7717279.39 25227.926326.42
River Rch & RM=10956,77,8498.046
 6319.4210225.3213949.69 17321.1 25288.826383.75
River Rch & RM=10956,77,8254.017
 6321.3110228.4913954.12 17326.725296.9826391.43
River Rch & RM=10956,77,8009.989
 6322.69 10230.813957.3417330.7825302.9426397.02
River Rch & RM=10956,77,7765.961
 6563.5210629.15   1450918024.0626315.1327328.24
River Rch & RM=10956,77,7521.933
 6570.4610640.8214525.3118044.73 26345.3 27356.5
River Rch & RM=10956,77,7277.905
 6573.6810646.2214532.8618054.2926359.2727369.58
River Rch & RM=10956,77, 6792.23
 6590.3210674.1414571.8818103.7226431.4427437.06
River Rch & RM=10956,77,6306.555
 6604.3610697.6414604.6618145.1926491.9727493.46
River Rch & RM=10956,77, 5728.55
 6657.6210786.3414728.0218300.8126719.1827703.55
River Rch & RM=10956,77,5335.205
 6666.2610800.7514748.0818326.1526756.1827737.82
River Rch & RM=10956,77, 4849.53
 6681.4210825.9814783.1618370.3826820.7527797.41
River Rch & RM=10956,77,4363.855
 6699.3410855.7214824.4518422.3826896.6727867.21
River Rch & RM=10956,77,4313.469
 6700.3810857.4614826.8618425.4226901.1127871.31
River Rch & RM=10956,77,4100.484
  6700.910858.3314828.0718426.9426903.3427873.37
Boundary for River Rch & Prof#=10956,77,1
Up Type= 0
Dn Type= 2
Boundary for River Rch & Prof#=10956,77,2
Up Type= 0
Dn Type= 2
Boundary for River Rch & Prof#=10956,77,2
Up Type= 0
Dn Type= 2
Boundary for River Rch & Prof#=10956,77,2
Up Type= 0
Dn Type= 2
Boundary for River Rch & Prof#=10956,77,2
Up Type= 0
Dn Type= 2
Boundary for River Rch & Prof#=10956,77,2
Up Type= 0
Dn Type= 2

--- 10956_ras.g01 (geometry) ---

Geom Title=10956
Program Version=4.10

River Reach=10956,77
Reach XY= 30
563661.803869665788664.577947244562105.242202282789485.423476905
562448.394549966790221.508540347 562525.12758413791313.329678029
561532.150203347 791751.39837195562133.632743597792253.344271347
562118.151416093792772.678307891561922.358711243  792967.4327925
561568.034452975792919.240238354561332.099003732793294.236713082
560623.439576328793713.539203942 560316.35622412794366.797811389
560476.745899945794510.830747679560887.538534135794295.586172462
561339.954493672794540.340243861561528.878803253 794857.20275186
561260.879529715795404.321472406561378.657705337795585.111918211
562144.978828371795460.628111124 562227.32084614795961.840623587
561884.760842949796555.436864004560977.249390423 797373.85500592
559402.920847148798303.200850099559323.508031726798903.871274456
558405.008511156800008.020553559557337.522619814 800383.80703932
557321.327813148801869.981721595556663.193991959 801871.07096985
555924.997174442801288.765072614555445.753909111 801706.23472321

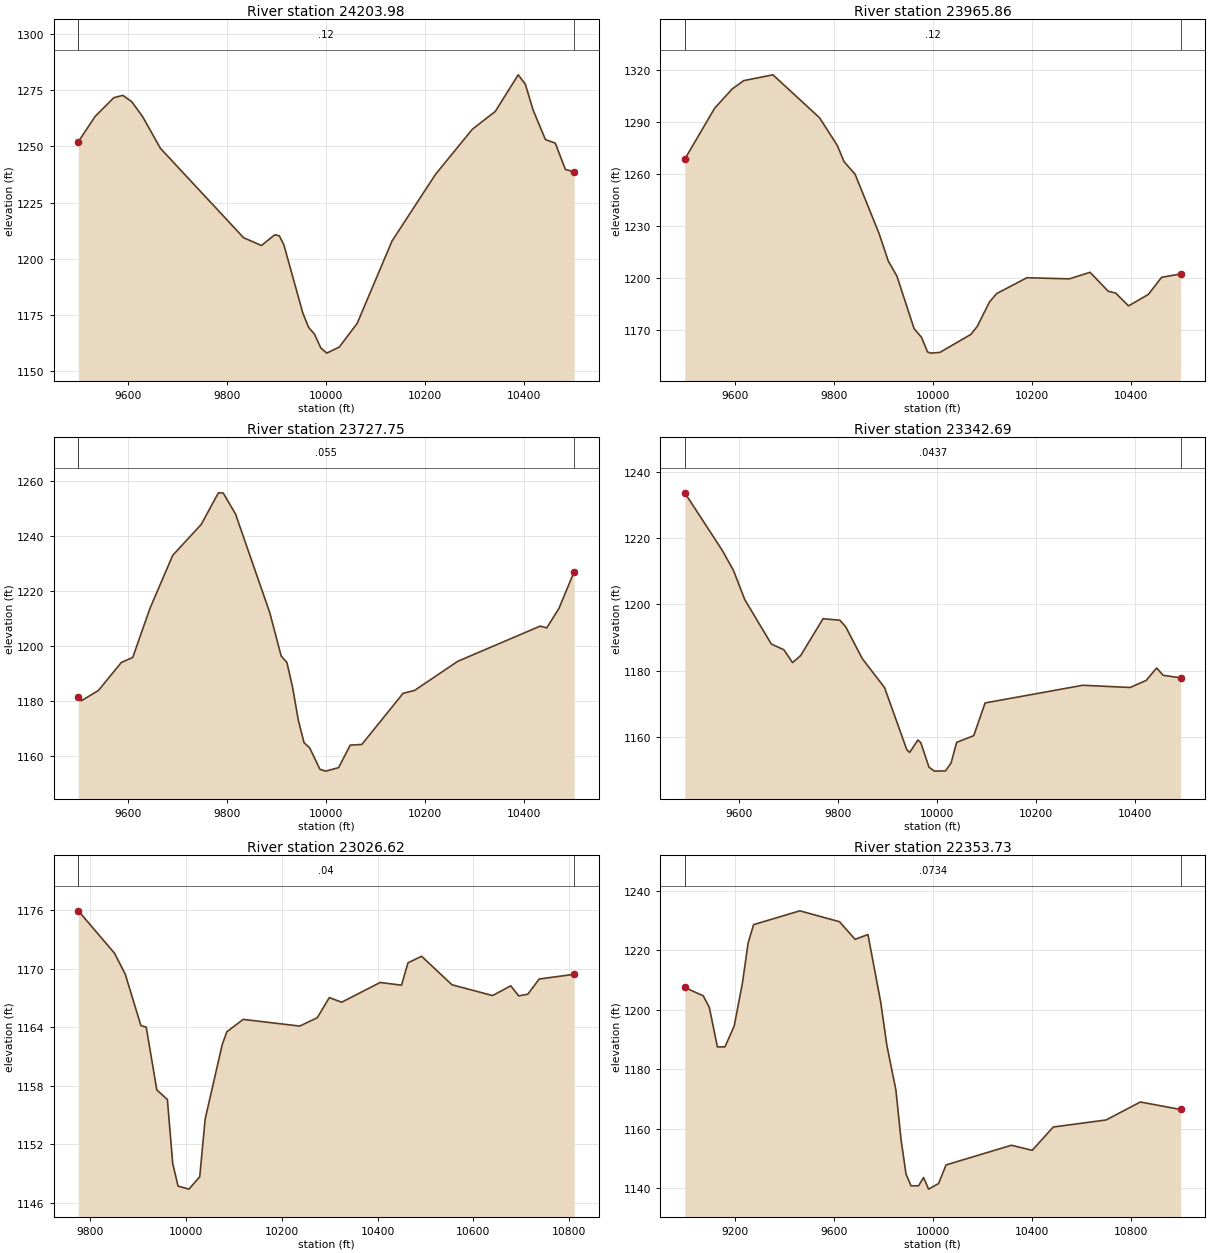
Type RM Length L Ch R = 1 ,24203.98,238.114700,238.114700,238.114700
XS GIS Cut Line= 6
563385.241135297788246.809447665563613.863975088788590.910616061
 563685.34703789788703.592804766563725.860734846788761.951425095
563838.648143611788907.646567881563970.539423271789058.075037128
#Sta/Elev= 30
9499.0061252.0829532.8511263.3339570.8511271.7039588.921 1272.749606.9911269.915
9628.8991263.2649664.917 1249.159833.001 1209.379869.0181205.9129896.1151210.696
9905.0361210.2429914.2521206.3019952.5141175.952 9964.361169.4839976.2061166.498
 9988.871160.358   100011158.00910026.261160.701 10062.51171.24310132.921207.899
10220.731237.55110295.04 1257.6210341.611265.59610387.971281.86910402.411277.645
10418.211266.10210442.88 1253.0710462.921251.45510483.341239.73310500.981238.737
#Mann= 3 , 0 , 0
9499.006    0.12       09499.006    0.12       010500.98    0.12       0
#XS Ineff= 2 , 0
       0                               0
Bank Sta=9499.006,10500.98
Exp/Cntr=0.3,0.1

Type RM Length L Ch R = 1 ,23965.86,238.114600,238.114600,238.114600
XS GIS Cut Line= 6
563193.828238091788383.806941382563339.167017163788617.285026337
563442.670030725788769.926308783563633.398643264789020.812979871
563713.910495511789118.418328486563780.923858488789193.741736599
#Sta/Elev= 30
9499.0111268.7439559.3131298.097 9594.651309.1869618.2091314.0349677.1051317.359
9771.3391292.6039807.2111276.6099821.0131267.2089843.1281260.039  9891.41226.006
9910.2631209.9499927.6861201.2549962.407 1170.969977.1841166.0749989.5961157.569
9996.1681156.86810014.551157.28810077.171167.67310089.691172.11910114.741186.386
10129.111191.18110190.38 1200.3510276.161199.69210317.961203.47610354.731192.537
10369.811191.48110395.731184.11310435.741190.69810462.51 1200.5710500.981202.544
#Mann= 3 , 0 , 0
9499.011    0.12       09499.011    0.12       010500.98    0.12       0
#XS Ineff= 2 , 0
       0                               0
Bank Sta=9499.011,10500.98
Exp/Cntr=0.3,0.1

Type RM Length L Ch R = 1 ,23727.75,385.053900,385.053900,385.053900
XS GIS Cut Line= 6
563018.879052929788499.732067254563262.529854006788922.849502943
563330.236565194789033.066732069563436.868864106 789183.31247694
563498.841323965789260.852365342563565.350305427789336.615021601
#Sta/Elev= 30
9499.0051181.3489505.0841180.0439539.7021183.804 9585.861193.9949608.9391195.831
9643.5581213.6139689.716 1233.039747.4131244.3139782.0321255.8139791.8191255.735
 9816.651248.1079885.8871212.1319908.9661196.3229920.5061194.0079932.0451184.874
9943.5851172.9399955.1241164.7569966.6641162.8369987.2611155.055    99991154.403
10024.921155.67110048.411163.864 10071.91164.12810155.271182.75910178.311183.798
10265.721194.41710432.281207.24610445.59 1206.6110470.111213.64510500.961227.042
#Mann= 3 , 0 , 0
9499.005   0.055       09499.005   0.055       010500.96   0.055       0
#XS Ineff= 2 , 0
       0                               0
Bank Sta=9499.005,10500.96
Exp/Cntr=0.3,0.1

Type RM Length L Ch R = 1 ,23342.69,316.076700,316.076700,316.076700
XS GIS Cut Line= 6
 562703.44853593788677.900304365562958.065656337789166.545072808
562996.939402255789234.329028255563050.135257387789316.783968684
563111.140604333789401.703282136563221.306509558789531.194950482
#Sta/Elev= 30
9490.806 1233.689566.6561216.2889589.2641210.2399611.8721201.4949665.7021188.047
9691.0011186.3249708.5941182.4499724.9131184.563 9770.131195.6919804.042 1195.24
9815.8251193.3039849.2591183.7019894.475  1174.99939.5251156.1159945.3771155.359
9961.8671159.1079967.8131158.2539984.209 1150.89 9995.411149.69810017.761149.774
10028.931152.16610040.111158.37910074.631160.39710097.691170.27210294.991175.606
10390.751174.93710423.121177.07510444.261180.81610457.651178.60210492.741177.861
#Mann= 3 , 0 , 0
9490.806  0.0437       09490.806  0.0437       010492.74  0.0437       0
#XS Ineff= 2 , 0
       0                               0
Bank Sta=9490.806,10492.74
Exp/Cntr=0.3,0.1

Type RM Length L Ch R = 1 ,23026.62,672.883600,672.883600,672.883600
XS GIS Cut Line= 6
 562553.98420733789046.538123878562701.345088306789347.482641528
562749.634622652789428.065141341562840.042349731789549.248597236
562974.016664257789676.851058251563198.080805162789824.523794462
#Sta/Elev= 30
9775.7871175.9449851.1191171.6069873.6621169.4499906.3671164.1699917.417 1164.02
9939.5161157.5769961.5841156.5929972.5981150.0619983.8141147.71410006.421147.404
10029.031148.66810040.341154.58910075.941162.22410085.561163.54110119.741164.811
10237.731164.12510274.271164.98510299.291167.04410325.021166.57110405.521168.598
10449.871168.31810463.461170.61410491.841171.28210555.251168.36110639.871167.255
10677.941168.25310694.391167.22110713.451167.39510737.071168.95110810.081169.435
#Mann= 3 , 0 , 0
9775.787    0.04       09775.787    0.04       010810.08    0.04       0
#XS Ineff= 2 , 0
       0                10495.37       0
Bank Sta=9775.787,10810.08
Exp/Cntr=0.3,0.1

Type RM Length L Ch R = 1 ,22353.73,546.982500,546.982500,546.982500
XS GIS Cut Line= 6
561150.150991718789196.173808333561450.337148286789354.526660632
561705.602599798789457.463763876561964.687486964789524.185797936
562352.830445679789570.502289548563037.581692132789815.325929818
#Sta/Elev= 30
8999.0761207.5079073.6981204.6879098.1491200.7869130.6991187.4849161.3241187.513
9198.6931194.5769232.1731209.1989254.4931222.3879276.8121228.6589463.5291233.308
9623.7761229.6389686.6591223.7119738.5421225.3269790.0941202.5289815.0851187.929
9851.4411172.9619871.8221156.4969892.1411144.704  9912.41140.733 9942.79 1140.73
 9963.051143.5259983.3091139.61210023.811141.50510053.841147.75810317.451154.378
10401.831152.67710486.761160.52410699.841162.89310838.341168.945 11000.91166.425
#Mann= 3 , 0 , 0
8999.076  0.0734       08999.076  0.0734       0 11000.9  0.0734       0
#XS Ineff= 2 , 0
       09948.691        10840.97       0
Bank Sta=8999.076,11000.9
Exp/Cntr=0.3,0.1

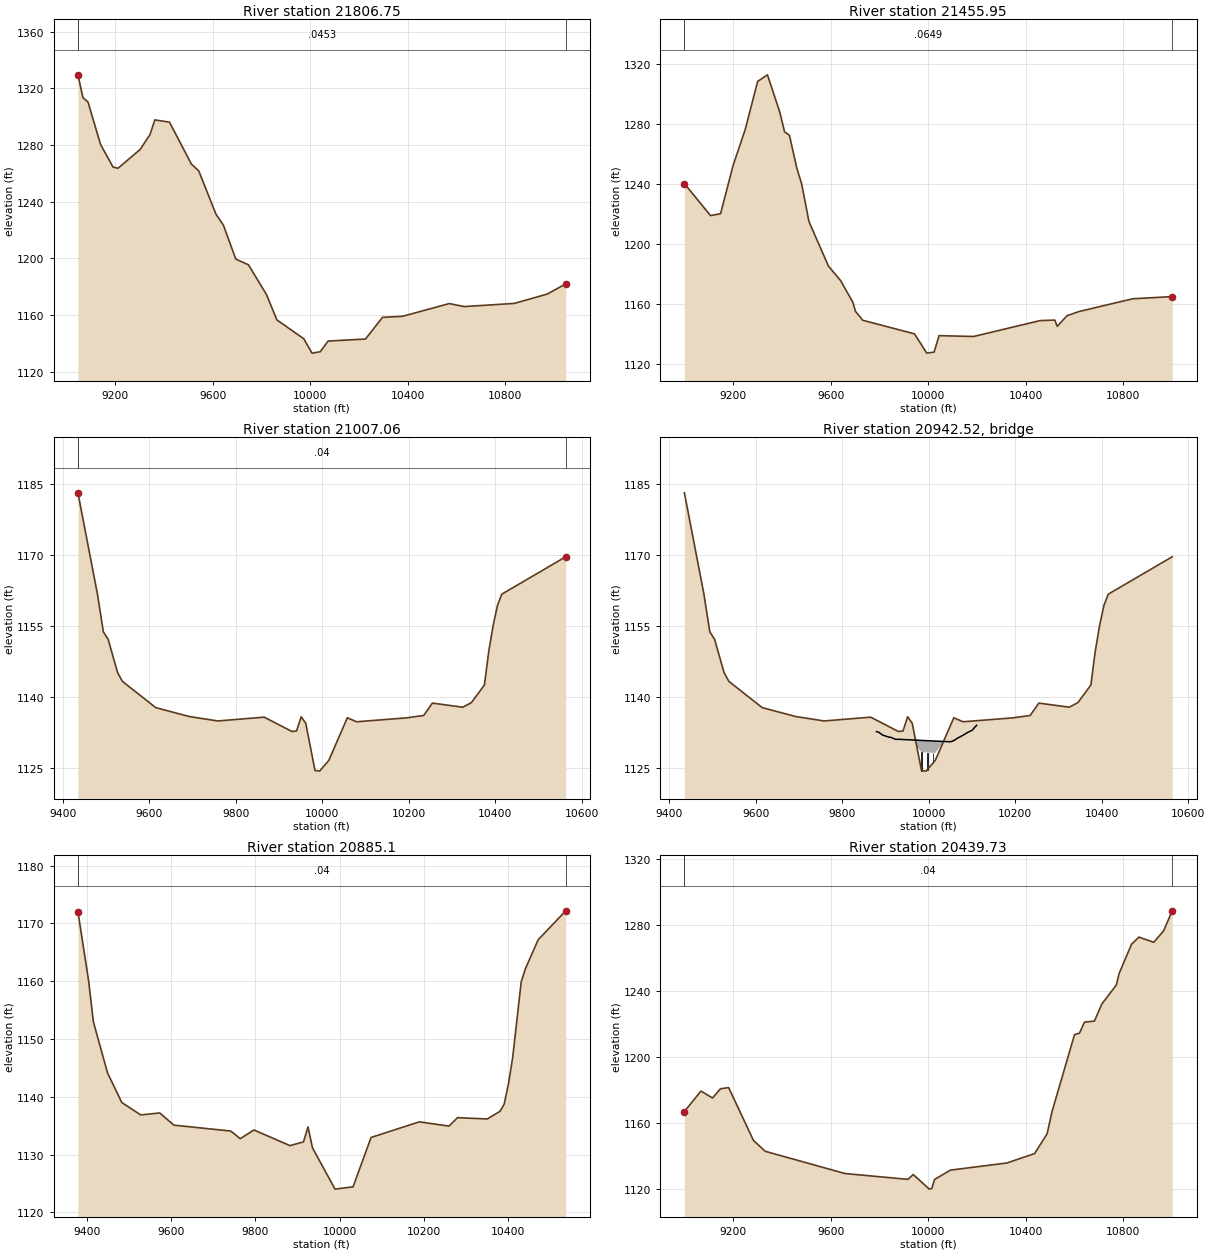
Type RM Length L Ch R = 1 ,21806.75,350.802300,350.802300,350.802300
XS GIS Cut Line= 6
561414.972460667790098.759097867561721.586940262790155.280952544
 561993.36890873790143.067747486562583.413500746789896.822547906
562752.656476375789860.207190372 563337.41519922 789984.85760948
#Sta/Elev= 30
9046.3931329.4339067.1091313.3279087.7971310.2119139.1761280.3159190.3251264.358
 9210.761263.4879301.7651276.7619341.9891287.2289362.0681297.6389422.1371296.024
9512.1791266.4219542.2611261.6429612.8331231.0689643.2481223.4099694.3241199.345
 9746.091195.391 9819.89 1174.479862.7581156.502 9973.071143.21110006.971133.037
10040.871134.025   10073 1141.5610226.441142.98910296.39  1158.310379.111159.032
10570.03 1168.0110630.871165.88910836.631168.10510972.351174.72111048.221181.881
#Mann= 3 , 0 , 0
9046.393  0.0453       09046.393  0.0453       011048.22  0.0453       0
#XS Ineff= 2 , 0
       0                10565.52       0
Bank Sta=9046.393,11048.22
Exp/Cntr=0.3,0.1

Type RM Length L Ch R = 1 ,21455.95,448.892400,448.892400,448.892400
XS GIS Cut Line= 6
561471.058220915790324.921376738561752.501075036790385.216040505
561981.384302593790397.828309484562970.704726538790268.991335805
563211.792762825790264.151966037563455.574104346790287.304171272
#Sta/Elev= 30
8999.0741240.3699106.3171219.0679147.4531220.3249198.3751252.1119249.2081276.679
9299.6831308.347 9339.881312.7369390.1151288.1619410.1291274.8019430.1441272.523
9460.1651250.8029480.1731240.2269510.1741215.1079590.2761185.4649640.5131175.723
 9690.791161.2439700.855 1155.459731.1821149.4039943.3551140.376 9993.711127.553
10023.94 1128.26 10044.1 1139.1910185.641138.61310458.651149.19710519.011149.547
10529.04  1145.410569.131152.44210619.151155.26810839.361163.73111000.931165.167
#Mann= 3 , 0 , 0
8999.074  0.0649       08999.074  0.0649       011000.93  0.0649       0
#XS Ineff= 2 , 0
       0                               0
Bank Sta=8999.074,11000.93
Exp/Cntr=0.3,0.1

Type RM Length L Ch R = 1 ,21007.06,121.960400,121.960400,121.960400
XS GIS Cut Line= 4
561981.598816514790716.101621374562300.712399989790863.332786724
562647.934622169790733.124453396563052.432149857790766.101621374
#Sta/Elev= 30
9434.9291183.227 9480.041161.828 9493.741153.8339504.7531152.2699526.7791145.191
9537.792 1143.379614.8831137.8249691.9741135.9469758.0531135.0029865.7091135.807
9929.7891132.7849940.4691132.8739951.1491135.8989961.8291134.5099983.1891124.541
9993.8691124.39810015.231126.69110057.951135.67810079.31 1134.8310194.391135.656
10234.521136.16210254.591138.77710324.821137.91310344.891138.88110374.991142.612
10385.021149.73110395.061155.15110405.091159.41410415.121161.80210563.04 1169.71
#Mann= 3 , 0 , 0
9434.929    0.04       09434.929    0.04       010563.04    0.04       0
#XS Ineff= 2 , 0
       0                               0
Bank Sta=9434.929,10563.04
Exp/Cntr=0.3,0.1

Type RM Length L Ch R = 3 ,20942.52,,,
BEGIN DESCRIPTION:
END DESCRIPTION:
Bridge Culvert--1,0,-1,-1, 0
Deck Dist Width WeirC Skew NumUp NumDn MinLoCord MaxHiCord MaxSubmerge Is_Ogee
53.106200,15.748000,2.6,0, 23, 23, , , 0.95, 0, 0,0,,
 9879.27 9884.23 9893.35 9897.37 9908.75 9910.52 9923.67 9923.93 9924.41 9927.66
 9972.34 9972.3410034.3510034.3510050.6110059.5610063.4210069.8610080.1710090.47
10100.7810104.8510110.69
 1132.74 1132.63 1132.01 1131.90 1131.55 1131.59 1131.11 1131.10 1131.09 1131.14
 1130.94 1130.94 1130.67 1130.67 1130.60 1130.92 1131.20 1131.53 1132.02 1132.61
 1133.05 1133.50 1134.10
  132.74  132.63  132.01  131.90  131.55  131.59  131.11  131.10  131.09  131.14
  130.94 1128.44 1128.17  130.67  130.60  130.92  131.20  131.53  132.02  132.61
  133.05  133.50  134.10
 9879.27 9884.23 9893.35 9897.37 9908.75 9910.52 9923.67 9923.93 9924.41 9927.66
 9976.07 9976.0710038.0810038.0810050.6110059.5610063.4210069.8610080.1710090.47
10100.7810104.8510110.69
 1132.74 1132.63 1132.01 1131.90 1131.55 1131.59 1131.11 1131.10 1131.09 1131.14
 1130.93 1130.93 1130.65 1130.65 1130.60 1130.92 1131.20 1131.53 1132.02 1132.61
 1133.05 1133.50 1134.10
  132.74  132.63  132.01  131.90  131.55  131.59  131.11  131.10  131.09  131.14
  130.93 1128.43 1128.15  130.65  130.60  130.92  131.20  131.53  132.02  132.61
  133.05  133.50  134.10
Pier Skew, UpSta & Num, DnSta & Num=  ,9984.14, 2 ,9987.88, 2 , 0 , 0 , 0 ,,
    2.00    2.00
  130.89 1130.89
    2.00    2.00
  130.87 1130.87
Pier Skew, UpSta & Num, DnSta & Num=  ,9996.94, 2 ,10000.68, 2 , 0 , 0 , 0 ,,
    2.00    2.00
  130.83 1130.83
    2.00    2.00
  130.82 1130.82
Pier Skew, UpSta & Num, DnSta & Num=  ,10009.74, 2 ,10013.48, 2 , 0 , 0 , 0 ,,
    2.00    2.00
  130.78 1130.78
    2.00    2.00
  130.76 1130.76
Pier Skew, UpSta & Num, DnSta & Num=  ,10022.54, 2 ,10026.28, 2 , 0 , 0 , 0 ,,
    2.00    2.00
  130.72 1130.72
    2.00    2.00
  130.70 1130.70
BR Coef=-1 , 0 , 0 ,, 0 ,,,0.8,0,1,0,
WSPro=,,,, 1 ,,,, 0 ,,,, 0 ,,,,-1 ,-1 ,-1 , 0 , 0 , 0 , 0 , 0
BC Design=,, 0 ,, 0 ,,,,,,

Type RM Length L Ch R = 1 , 20885.1,445.361800,445.361800,445.361800
XS GIS Cut Line= 4
561952.432149857790811.934954703562300.712399989790990.416120023
562642.726288825790861.249453381563039.932149857790907.768288046
#Sta/Elev= 30
 9379.391172.0429404.7481160.0679415.9851153.0029449.6951144.1259483.4051139.015
9528.3511136.8689573.2981137.2079607.0081135.1029741.8471134.0769764.3211132.754
9796.7011134.2669882.2161131.5549914.2851132.2019924.9741134.7889935.6631131.165
 9989.111124.02510031.871124.42610074.631132.96910188.961135.66910259.441134.931
10279.581136.39510350.061136.16810380.261137.48810390.33 1138.76 10400.4 1142.26
10410.471146.836 10430.61159.90310440.671162.19110470.881167.19310536.251172.192
#Mann= 3 , 0 , 0
 9379.39    0.04       0 9379.39    0.04       010536.25    0.04       0
#XS Ineff= 2 , 0
       0                               0
Bank Sta=9379.39,10536.25
Exp/Cntr=0.3,0.1

Type RM Length L Ch R = 1 ,20439.73,1336.085400,1336.085400,1336.085400
XS GIS Cut Line= 6
561698.155840786790773.654558711561929.107263792 790933.57847217
562293.769406736791231.643720728562484.673029196791340.712332749
562917.709289289 791486.48952499563479.835537396791592.703097995
#Sta/Elev= 30
8999.0691166.7479066.9161179.1749114.6591174.9559146.7471180.5249180.6841181.279
9282.3611149.257 9330.431142.6459657.9381129.1429916.0081125.6129938.2821128.527
10004.08 1119.6810014.841120.15610025.591125.54510090.751131.207 10322.41135.541
10436.21 1141.2310487.491153.23610508.011166.86610600.091213.40510620.481214.288
10640.881220.97210681.59 1221.6210712.071231.93610771.451243.49610783.191250.527
10833.931268.20410864.331272.56210925.131269.41410965.661276.34211000.961288.493
#Mann= 3 , 0 , 0
8999.069    0.04       08999.069    0.04       011000.96    0.04       0
#XS Ineff= 2 , 0
       0                               0
Bank Sta=8999.069,11000.96
Exp/Cntr=0.3,0.1

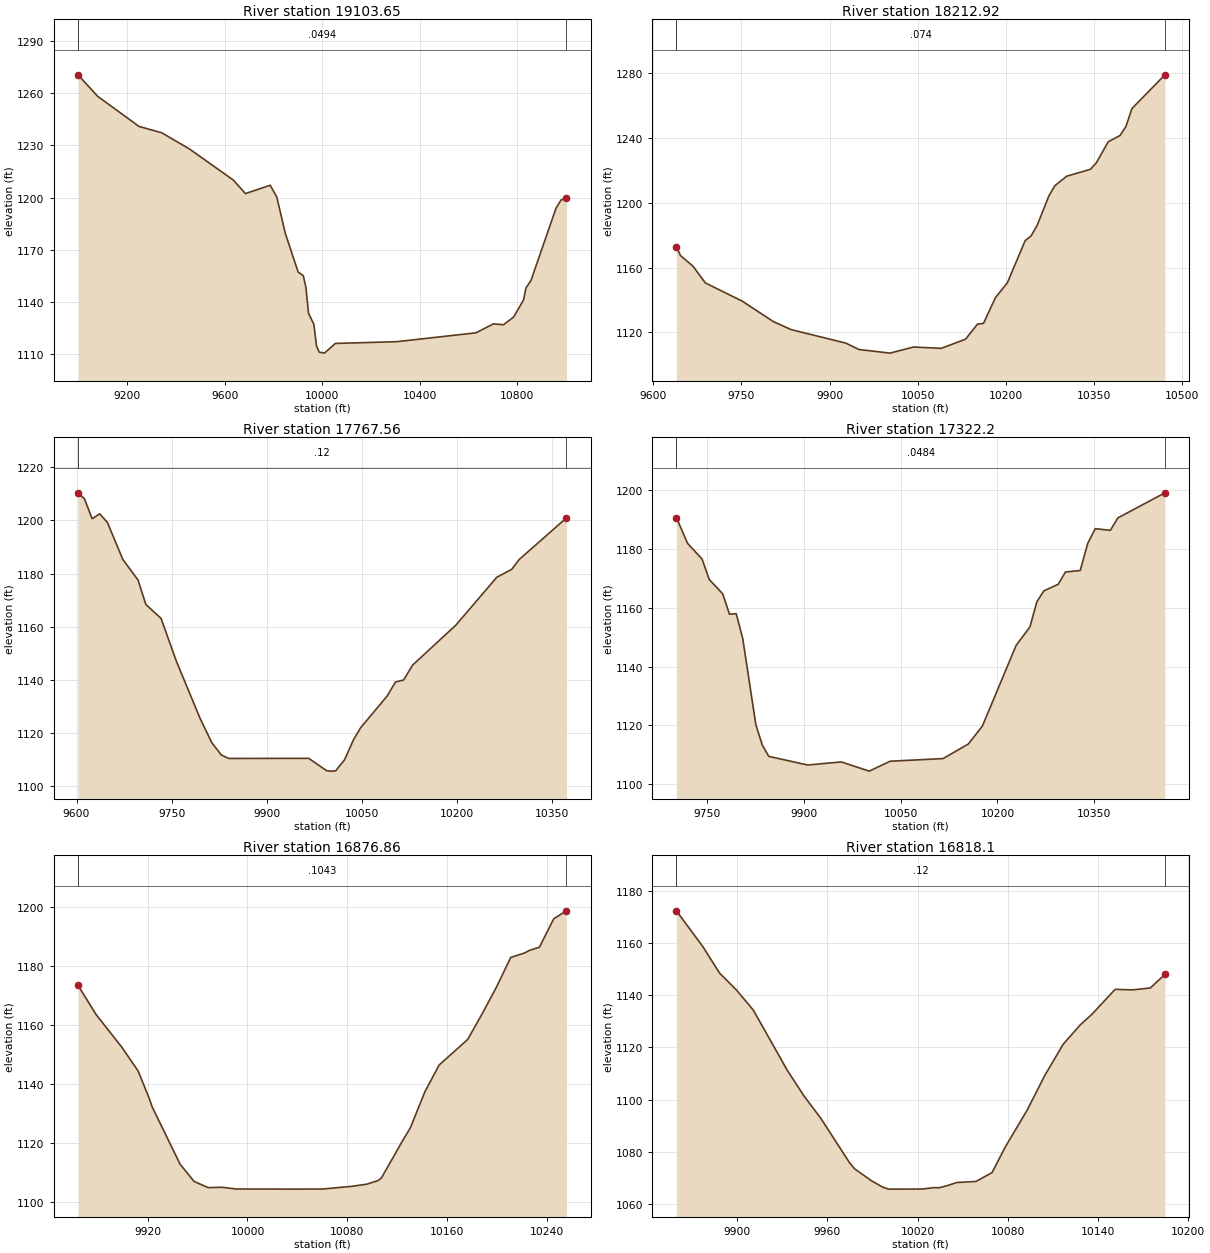
Type RM Length L Ch R = 1 ,19103.65,890.723600,890.723600,890.723600
XS GIS Cut Line= 6
560599.246107928791835.997032486560944.051651605 791948.86301718
561228.140556413791978.270267126561450.395351397791938.254475477
561793.694835365 791796.34511574562526.916313112  791962.3596003
#Sta/Elev= 30
8999.1151270.4919080.3131258.1129249.3121240.8859342.6791237.1999454.7611228.059
9635.5221210.1099685.6211202.3299786.812 1207.129813.8251200.3949848.7791179.533
9901.3211157.3229922.5721155.1679933.2311148.4699944.0691133.6189965.747 1127.34
9976.5861114.9169987.4241111.33410009.161110.75810053.671116.31910305.751117.325
 10630.21122.42110701.911127.55910742.891127.04610783.871131.41210824.851141.199
10835.091148.20210855.581152.47410958.031193.89310978.521198.62811000.971199.618
#Mann= 3 , 0 , 0
8999.115  0.0494       08999.115  0.0494       011000.97  0.0494       0
#XS Ineff= 2 , 0
       0                               0
Bank Sta=8999.115,11000.97
Exp/Cntr=0.3,0.1

Type RM Length L Ch R = 1 ,18212.92,445.361800,445.361800,445.361800
XS GIS Cut Line= 6
561798.460794642792425.727571779561963.290852996 792371.74441794
562033.465616548792368.219733004562094.102030346792393.799191374
562182.579631602792480.922598062562570.417205165792544.743005606
#Sta/Elev= 30
9639.5161173.0229646.4581167.4669667.6881160.9189688.9181150.5449751.461 1139.35
9804.4621126.7199834.9911121.7379927.6991113.4439950.0651109.49210002.851107.255
10043.051111.03810089.971110.19910131.411115.85910151.761125.18410161.941125.602
 10182.31141.54210202.571150.66810232.841176.68510242.921179.55810253.011185.923
10273.191204.27210283.28 1210.5410303.461216.42610343.811220.659 10353.91224.702
10374.081237.63910394.261241.54610404.341247.17210414.431258.15710470.511278.966
#Mann= 3 , 0 , 0
9639.516   0.074       09639.516   0.074       010470.51   0.074       0
#XS Ineff= 2 , 0
       0                               0
Bank Sta=9639.516,10470.51
Exp/Cntr=0.3,0.1

Type RM Length L Ch R = 1 ,17767.56,445.361800,445.361800,445.361800
XS GIS Cut Line= 6
561746.522151792792598.357564726561990.643836394792757.915966504
562026.603479486792786.204769842 562158.73291604792909.615965553
562265.952943688792985.437153006562368.450670024793048.715649643
#Sta/Elev= 30
9602.2491210.4169612.4931208.1899624.5751200.6729636.6581202.498 9648.741199.222
9672.9051185.3529697.0711177.5149709.1531168.4089733.3181163.0739757.3431147.001
9794.4991125.588 9813.291116.2689828.2111111.6399840.0221110.329 9966.111110.376
9994.2261105.731   100011105.55510008.451105.63610022.521109.81210036.661117.357
10048.011121.94210089.751133.85410102.781139.10110115.811139.91310129.751145.473
10198.021160.55210262.651178.61610286.15 1181.59 10297.91185.29110372.471200.982
#Mann= 3 , 0 , 0
9602.249    0.12       09602.249    0.12       010372.47    0.12       0
#XS Ineff= 2 , 0
       0                               0
Bank Sta=9602.249,10372.47
Exp/Cntr=0.3,0.1

Type RM Length L Ch R = 1 , 17322.2,445.343200,445.343200,445.343200
XS GIS Cut Line= 6
561680.476829786792650.088540738561722.847691915 792811.28488047
561664.007963904793002.168277558561664.164736436793083.858535527
561698.084236679793190.574687879561797.685930311793354.875131983
#Sta/Elev= 30
9702.4151190.6879719.7931181.9179742.2561176.5949753.2141169.6729774.2161164.777
9784.7171157.8299795.186    11589805.315 1149.489825.5711120.2369835.6261113.289
9845.6271109.4729905.9871106.5349957.8381107.59210001.321104.45610033.641107.821
10115.781108.72210154.821113.67310176.571119.74910228.941147.20310250.351153.519
10261.061162.05110271.971165.77610294.26 1168.0210305.411172.18410328.281172.702
10339.951181.92410351.611186.93510374.951186.35810386.621190.58410459.521199.118
#Mann= 3 , 0 , 0
9702.415  0.0484       09702.415  0.0484       010459.52  0.0484       0
#XS Ineff= 2 , 0
       0                               0
Bank Sta=9702.415,10459.52
Exp/Cntr=0.3,0.1

Type RM Length L Ch R = 1 ,16876.86,58.759900,58.759900,58.759900
XS GIS Cut Line= 4
561262.066907078793108.948275164561384.260853589793171.364931554
561486.464895159793233.376372531561603.863782108793299.920497403
#Sta/Elev= 30
9864.0991173.4249878.622  1163.59899.3861152.3349912.3091144.3599921.3691134.895
9923.5381132.1979945.9961112.6979957.2251106.8359968.4541104.7549979.6831104.866
9990.9121104.28410037.271104.23510060.66 1104.2810084.051105.20510095.751105.925
10104.711107.12910107.451108.05910124.151120.48210130.671125.08610142.161137.173
10153.661146.34410176.651155.05510188.141163.69710199.641172.78110211.131182.873
10222.631184.44510225.551185.17210234.121186.35610245.611196.002 10255.81198.689
#Mann= 3 , 0 , 0
9864.099  0.1043       09864.099  0.1043       0 10255.8  0.1043       0
#XS Ineff= 2 , 0
       0                               0
Bank Sta=9864.099,10255.8
Exp/Cntr=0.3,0.1

Type RM Length L Ch R = 1 , 16818.1,244.028100,244.028100,244.028100
XS GIS Cut Line= 3
 561239.41749385793162.722965866 561391.66077733 793240.38169907
561523.318315476793319.973420948
#Sta/Elev= 30
9859.6991172.4419877.1921158.7919888.4181148.5569899.6441142.0599910.8691134.319
9933.3211111.3469944.5471101.3949955.773 1092.779974.747 1075.839978.225 1073.42
 9989.451068.8419996.7541066.44210000.681065.64610023.131065.66810030.61 1066.21
10034.511066.18910039.531066.95310046.191068.19410058.861068.58810069.561071.997
10078.19 1081.6610092.931096.01210104.621109.27510116.851121.26310127.991128.568
10136.181132.88410151.361142.30610163.051142.10910174.731142.83810184.451148.027
#Mann= 3 , 0 , 0
9859.699    0.12       09859.699    0.12       010184.45    0.12       0
#XS Ineff= 2 , 0
       0                               0
Bank Sta=9859.699,10184.45
Exp/Cntr=0.3,0.1

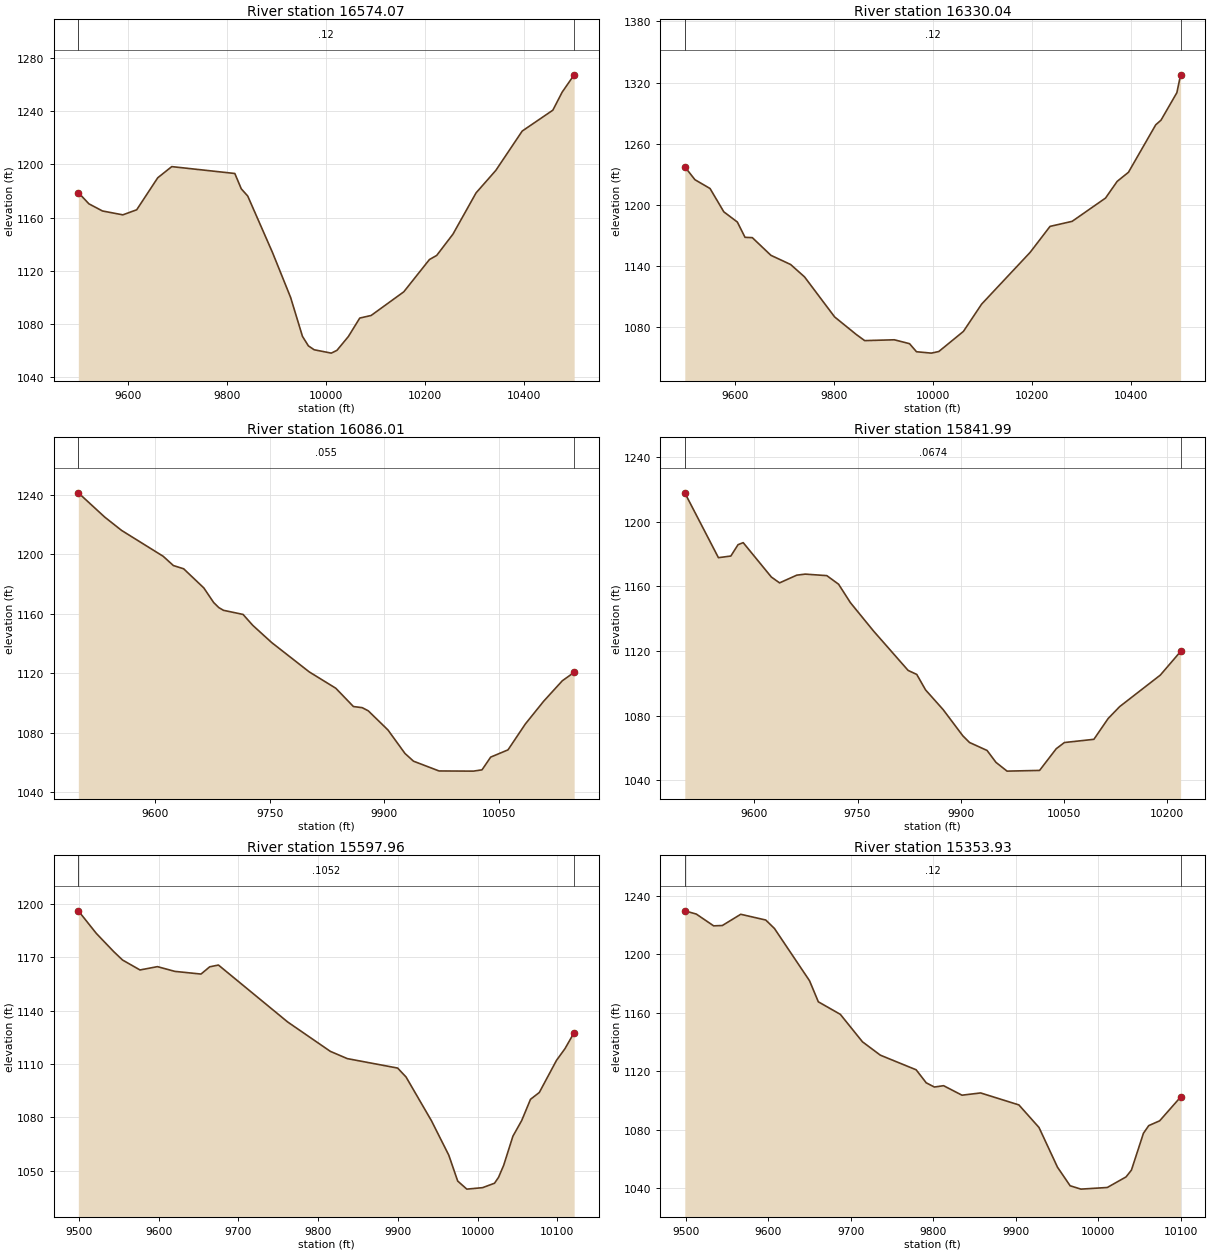
Type RM Length L Ch R = 1 ,16574.07,244.028200,244.028200,244.028200
XS GIS Cut Line= 6
 560849.41301816792959.031186208561091.106940773793209.850120211
561252.993873721793468.543468308561322.351354173793559.634970829
561411.471681452793645.405293854561501.506661301793707.318719023
#Sta/Elev= 30
 9499.05 1178.829520.4291170.3629547.8611164.9799589.0091162.0669616.9941165.883
9659.4881189.9629687.818 1198.379815.2621193.1979828.3111181.645 9841.361176.213
9891.5381133.5939927.9911099.9189951.9431070.6139963.9191063.4519975.5531060.525
10010.151057.98810021.661060.09110044.681070.472 10067.71084.37410090.721086.332
10156.691104.13710208.49 1128.4210223.141131.50510256.091147.57510302.731178.599
10342.64 1195.5210395.991225.14110457.891240.85310476.76 1254.4610500.931267.455
#Mann= 3 , 0 , 0
 9499.05    0.12       0 9499.05    0.12       010500.93    0.12       0
#XS Ineff= 2 , 0
       0                               0
Bank Sta=9499.05,10500.93
Exp/Cntr=0.3,0.1

Type RM Length L Ch R = 1 ,16330.04,244.028200,244.028200,244.028200
XS GIS Cut Line= 6
560670.607613806793138.681872609560780.129266419793253.511567899
561018.949320782793523.484918635561151.439210632 793656.16881645
561277.061724652793751.468954059561402.146744323 793807.43826112
#Sta/Elev= 30
9499.0151237.3459519.5141224.6459550.0181216.0159577.9161193.0889605.1931183.106
9620.7641168.071 9635.471167.7769672.9851150.4389712.8491141.423 9741.041129.218
 9801.781089.9439845.7321072.632 9862.521066.6889922.3751067.5039953.1251063.683
9967.182 1055.789997.0541054.40710012.221055.97110061.981075.71310098.871102.547
10196.761153.27910237.071178.82110281.76 1183.7910349.171206.61610372.711223.014
10395.551231.956 10450.61278.52210461.271283.093 10493.31310.05310500.931327.612
#Mann= 3 , 0 , 0
9499.015    0.12       09499.015    0.12       010500.93    0.12       0
#XS Ineff= 2 , 0
       0 9925.94                       0
Bank Sta=9499.015,10500.93
Exp/Cntr=0.3,0.1

Type RM Length L Ch R = 1 ,16086.01,244.028200,244.028200,244.028200
XS GIS Cut Line= 6
560530.711737221793254.777121226560636.885187628 793367.74831004
560710.512774376793463.441000983 560764.96722241793551.800893718
560860.251018321793737.913781138560895.532263136793787.156923868
#Sta/Elev= 30
9499.0551241.4639533.5981225.1479555.6221216.1979610.1581198.7639623.5871192.518
9637.0151190.3339663.4481177.4439676.2921167.6419683.0021164.2489689.1361162.398
9714.8231159.613 9727.391152.3449752.1141140.7699801.529 1120.939836.2761109.942
9859.3531097.6319870.8921096.8579878.8141094.7379904.6111081.8569926.9151066.028
9938.0671060.8389971.5231054.26110016.451054.149 10027.81055.00710039.151063.581
10061.851068.46910084.551085.86710108.621101.23610132.931114.94510148.491120.634
#Mann= 3 , 0 , 0
9499.055   0.055       09499.055   0.055       010148.49   0.055       0
#XS Ineff= 2 , 0
       0                               0
Bank Sta=9499.055,10148.49
Exp/Cntr=0.3,0.1

Type RM Length L Ch R = 1 ,15841.99,244.028100,244.028100,244.028100
XS GIS Cut Line= 6
560200.651422168793447.856271597560295.594599121793511.291118497
 560396.83326875793583.936831562 560624.40870689793760.979464263
560712.778840815793811.865184787560790.058091109793860.297762189
#Sta/Elev= 30
9499.0161217.7379547.875 1177.649565.8761178.6479576.4051185.6919583.8761186.932
9624.777 1165.679636.715 1162.069661.7011166.8329674.0091167.4729705.3251166.536
9722.4781161.2229739.5621149.8639773.205  1132.39823.475 1107.939836.0441105.442
9848.8131095.8859874.3521083.6949902.8771067.5429912.6591063.3789938.198 1058.43
 9951.121051.075  9967.21045.66210014.46  1046.1 10038.71059.53510050.531063.341
10093.361065.328   101141078.15810130.791085.541 10189.81105.01410219.371119.652
#Mann= 3 , 0 , 0
9499.016  0.0674       09499.016  0.0674       010219.37  0.0674       0
#XS Ineff= 2 , 0
       0                               0
Bank Sta=9499.016,10219.37
Exp/Cntr=0.3,0.1

Type RM Length L Ch R = 1 ,15597.96,244.028200,244.028200,244.028200
XS GIS Cut Line= 6
560114.228581289793760.532443312560360.581258327793867.979572152
560536.516277921793930.222601999560616.018295317793974.616013372
560654.371335927793992.405139972560685.889054052 794003.53139422
#Sta/Elev= 30
9499.0331196.1489521.7491183.3689543.6211173.1129554.5581168.451 9576.431162.867
9598.3031164.7379620.1751162.0699652.9841160.564 9663.921164.6429674.8571165.638
9761.7471133.5929815.297 1117.069836.6341112.9669899.7561107.6559910.2761102.642
9942.1591078.034 9963.951058.6259975.1171044.0649986.5891039.52310006.371040.351
10021.291042.84410026.35 1046.1410032.84 1052.9510044.391069.29810055.47 1078.16
10066.49 1090.0710077.521093.90310099.121112.00310109.721118.55410121.271127.643
#Mann= 3 , 0 , 0
9499.033  0.1052       09499.033  0.1052       010121.27  0.1052       0
#XS Ineff= 2 , 0
       0                               0
Bank Sta=9499.033,10121.27
Exp/Cntr=0.3,0.1

Type RM Length L Ch R = 1 ,15353.93,244.028200,244.028200,244.028200
XS GIS Cut Line= 6
560001.748128172793943.982482349560191.179216665794009.057285428
560271.402452574794042.673113121560329.205251131 794071.19648365
560413.967968224794125.498905041560524.594121969794224.240941409
#Sta/Elev= 30
 9499.071229.7499513.0091227.5329534.0461219.4679544.5651219.7019566.8481227.384
9597.1571223.4599607.6751217.7079650.244  1181.99660.8881167.4989687.5511158.923
9714.3811140.1229736.0661130.9789779.4361120.9829791.6361112.0699801.5411109.189
9812.6921110.0969834.9951103.5979857.5541105.1389903.937 1096.959928.3391081.488
 9950.731054.3239966.0511041.6189979.1571039.32310011.131040.45210033.82 1047.69
 10040.31052.31710054.88 1077.55 10061.3 1082.7810074.541086.06710099.941102.341
#Mann= 3 , 0 , 0
 9499.07    0.12       0 9499.07    0.12       010099.94    0.12       0
#XS Ineff= 2 , 0
       0                               0
Bank Sta=9499.07,10099.94
Exp/Cntr=0.3,0.1

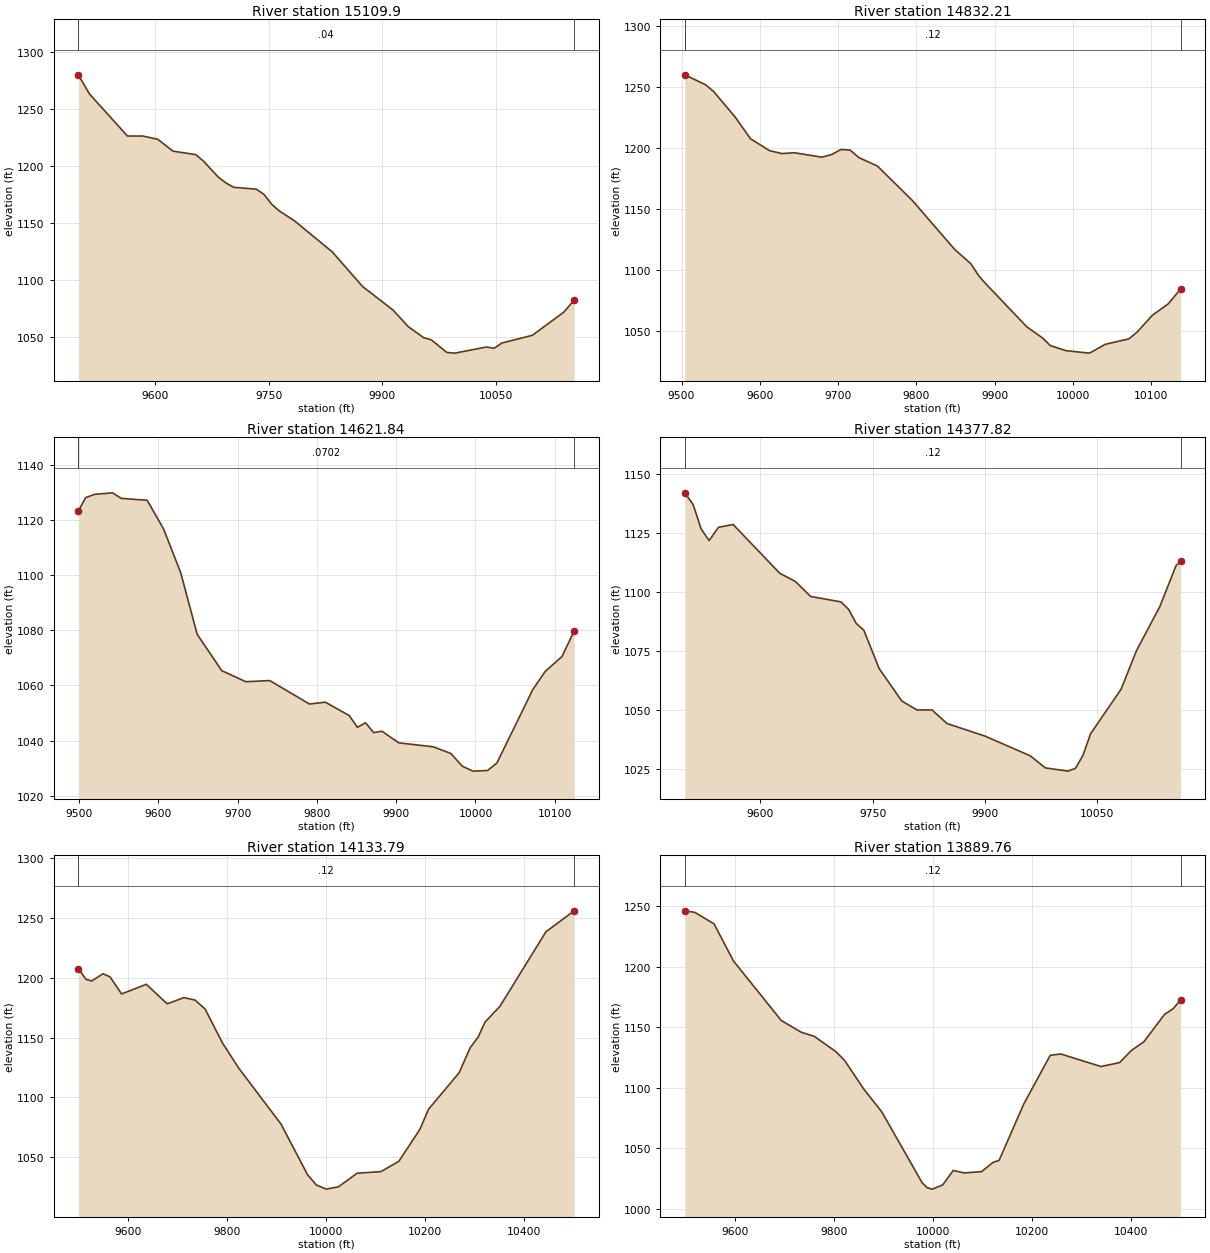
Type RM Length L Ch R = 1 , 15109.9,277.691400,277.691400,277.691400
XS GIS Cut Line= 6
559820.212335527794345.096501172560183.974009335794339.842397749
560279.392370909794349.833984509560383.317167699794376.076685309
560413.506774157794377.646197587560467.796073735794362.203483507
#Sta/Elev= 30
9499.0551280.1529513.8491263.2889563.8681226.4719583.8761226.4919603.884 1223.63
9623.8921213.2269653.904 1210.169663.9081204.6179683.9151190.2259693.9191185.267
9703.9231181.5179733.9351179.8719743.939 1175.27 9753.941166.784 9763.941160.854
9783.9421152.2239833.9471124.892 9873.981094.5149914.0941073.8499934.2831059.257
9954.4761049.621 9964.65 1047.729985.1221036.673 9995.64 1036.0810037.261041.426
10047.491040.35710057.721044.96610097.981051.73510139.521072.116   101531082.702
#Mann= 3 , 0 , 0
9499.055    0.04       09499.055    0.04       0   10153    0.04       0
#XS Ineff= 2 , 0
       0                               0
Bank Sta=9499.055,10153
Exp/Cntr=0.3,0.1

Type RM Length L Ch R = 1 ,14832.21,210.364900,210.364900,210.364900
XS GIS Cut Line= 6
560268.313378864794933.284873975560385.403195207794806.889417582
560426.115402645794742.878488836560457.258124618794675.406367786
560484.673325193794559.428509585560482.152660981794369.405915359
#Sta/Elev= 30
9504.1791259.8719530.7271251.7429540.9891246.2179568.5761225.2029588.1341207.429
9612.2381197.7579628.0071195.3189644.113 1195.999679.0931192.3559691.2611194.374
 9703.431198.6299715.1541198.2349726.8391191.888 9750.211185.0579795.0931156.645
9848.6231116.8589869.4781105.0079879.8381094.856 9888.091088.8769940.8621053.304
9960.9681044.1399970.9881037.874 9991.031033.68610021.041031.68910041.121038.894
10071.261043.38410081.311048.62510101.411062.77910121.51 1072.0410137.38 1084.24
#Mann= 3 , 0 , 0
9504.179    0.12       09504.179    0.12       010137.38    0.12       0
#XS Ineff= 2 , 0
       0                               0
Bank Sta=9504.179,10137.38
Exp/Cntr=0.3,0.1

Type RM Length L Ch R = 1 ,14621.84,244.028200,244.028200,244.028200
XS GIS Cut Line= 6
560663.453729351794883.119923451560725.121296768794728.612806794
560736.205206154794654.498027521 560734.80325168794577.591739355
560707.009904074794472.073273627560608.547089151794301.717990412
#Sta/Elev= 30
9499.1521123.1769508.3751128.0449519.7331129.2229542.3251129.782 9553.321127.765
9585.987 1127.089606.6211116.714 9628.221100.883 9649.04 1078.499679.9821065.338
9710.3621061.3199740.5831061.7329790.6161053.2229810.6621053.8959840.9391049.027
9851.0931044.7739861.3541046.4319871.6141042.8639882.1261043.3619903.2841039.153
9946.6351037.7369969.0061035.2939983.3761030.7039996.8771028.90510015.281029.132
10027.08 1031.8710072.241058.43610087.871065.00610109.17 1070.4710124.461079.733
#Mann= 3 , 0 , 0
9499.152  0.0702       09499.152  0.0702       010124.46  0.0702       0
#XS Ineff= 2 , 0
       0                               0
Bank Sta=9499.152,10124.46
Exp/Cntr=0.3,0.1

Type RM Length L Ch R = 1 ,14377.82,244.028200,244.028200,244.028200
XS GIS Cut Line= 6
560789.170970863794785.431550677560814.949427936794716.718297495
560835.529839959794639.159846257560853.887841369794536.435976817
560893.358851561794239.731947657560922.142608354794139.179923749
#Sta/Elev= 30
9499.0951141.9899510.2361136.9969520.9171126.6889531.5971121.7619544.1591127.386
9563.6391128.5539625.9921107.8549646.6841104.4259667.1111098.0519707.7451095.727
9717.9031092.5619728.062 1086.61 9738.221083.7179758.5281067.5599788.8151053.728
9809.0071049.9119829.1981049.926 9849.39 1044.149899.8681038.8299960.4431030.476
9980.6321025.32710010.781023.95810020.851025.13310030.961030.71210041.08  1039.8
10081.921058.75210102.461075.11510133.631093.79410155.011110.98210161.33 1113.01
#Mann= 3 , 0 , 0
9499.095    0.12       09499.095    0.12       010161.33    0.12       0
#XS Ineff= 2 , 0
       0                               0
Bank Sta=9499.095,10161.33
Exp/Cntr=0.3,0.1

Type RM Length L Ch R = 1 ,14133.79,244.028200,244.028200,244.028200
XS GIS Cut Line= 6
560815.878388565794886.917801575560891.487123958794772.420391028
561016.658329865794526.801752173561190.203883653794276.844165026
561286.542640081794159.774760967561390.127348408794077.446731185
#Sta/Elev= 30
 9499.071207.7549514.6731198.7019526.0851197.3789548.8841203.4059563.0621200.791
9586.5231186.5049636.3811194.5779678.6561178.2729712.3121183.4569734.5111181.453
9755.1771173.9749790.0071145.8079823.3051124.4479908.7381077.6779962.3581035.345
9980.0071026.8639999.9161023.387 10024.91025.36810062.341036.66210110.571038.018
10146.641046.62410189.161073.27410206.751090.16410268.621120.71910290.811141.581
10306.981150.48210320.521162.81410351.271176.346 10443.81238.43610500.931255.984
#Mann= 3 , 0 , 0
 9499.07    0.12       0 9499.07    0.12       010500.93    0.12       0
#XS Ineff= 2 , 0
       0                               0
Bank Sta=9499.07,10500.93
Exp/Cntr=0.3,0.1

Type RM Length L Ch R = 1 ,13889.76,140.000900,140.000900,140.000900
XS GIS Cut Line= 6
560979.195770873794895.363543985561190.474822399794686.686010232
561337.590591036794419.906201052 561406.98968602794328.155418733
561504.216462101794237.492490178561629.891652101794158.126542154
#Sta/Elev= 30
9499.1141246.2759519.4891244.9969558.1651235.5329597.6121204.7419694.0761155.632
9735.0711145.8269760.7051142.5869804.7891129.7899822.0121122.6239860.4791099.167
9897.2211080.0979978.4961021.7069988.9181017.4079999.3361016.31610020.191019.795
10041.581031.76110063.711029.69810098.581030.73710121.931038.404 10134.11040.063
10184.011086.67110237.471126.93110258.771127.98610339.941117.62610377.461120.849
10401.941131.08610426.391137.93610468.221160.624   104861165.46810500.881172.795
#Mann= 3 , 0 , 0
9499.114    0.12       09499.114    0.12       010500.88    0.12       0
#XS Ineff= 2 , 0
       0                               0
Bank Sta=9499.114,10500.88
Exp/Cntr=0.3,0.1