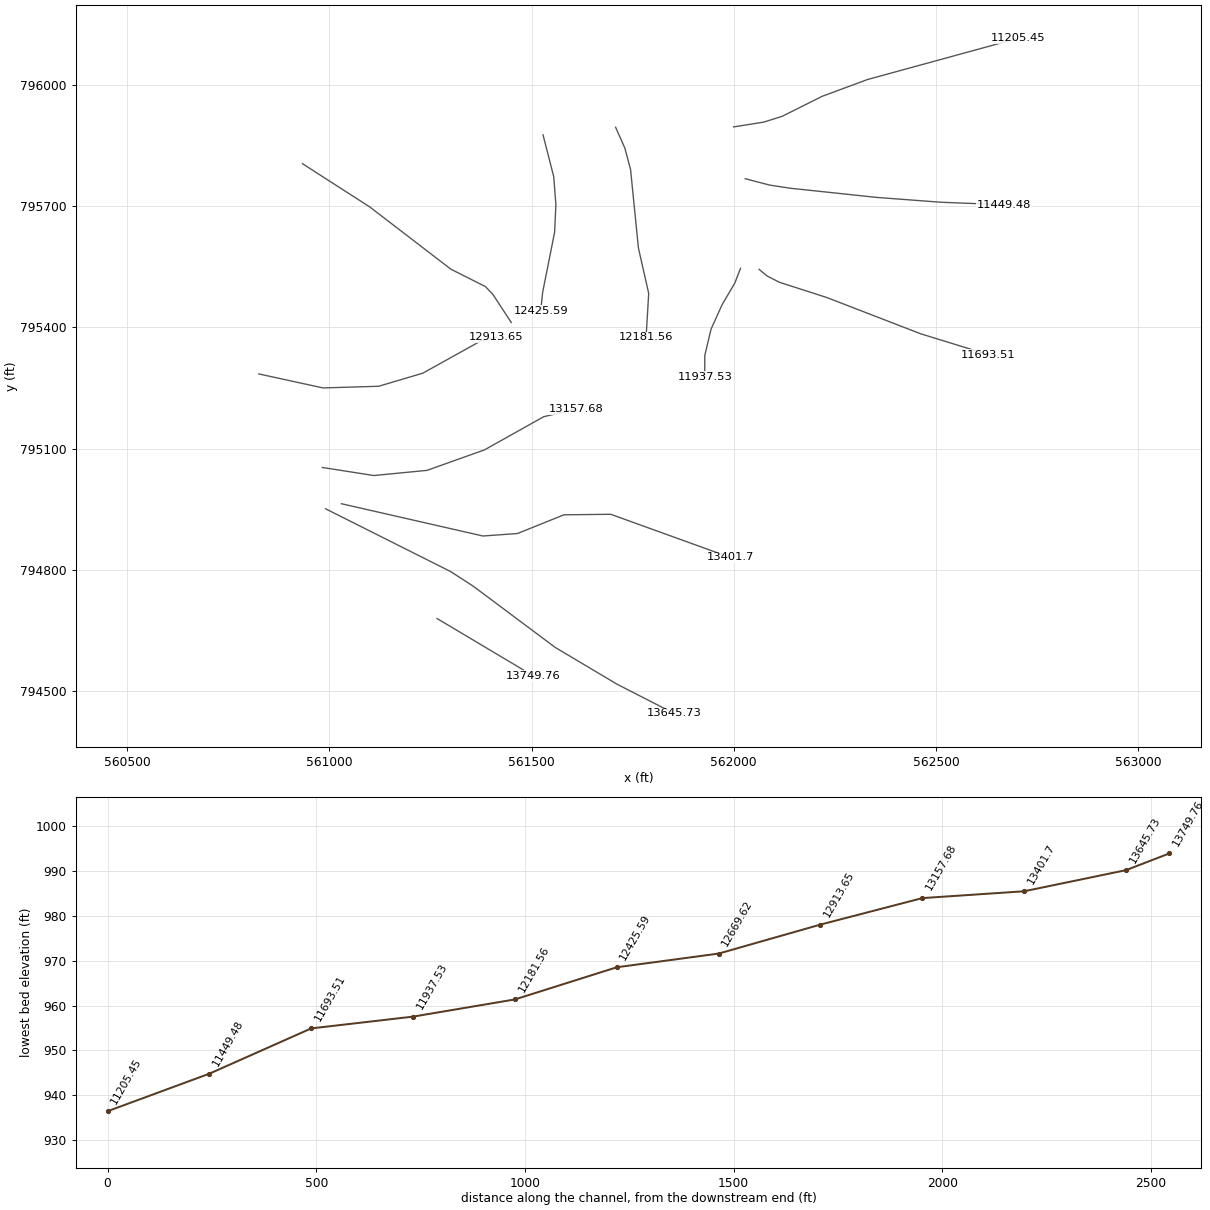
HEC-RAS study 10956_ras.prj: 10956

--- 10956_ras.g01 (geometry) --- (continued)

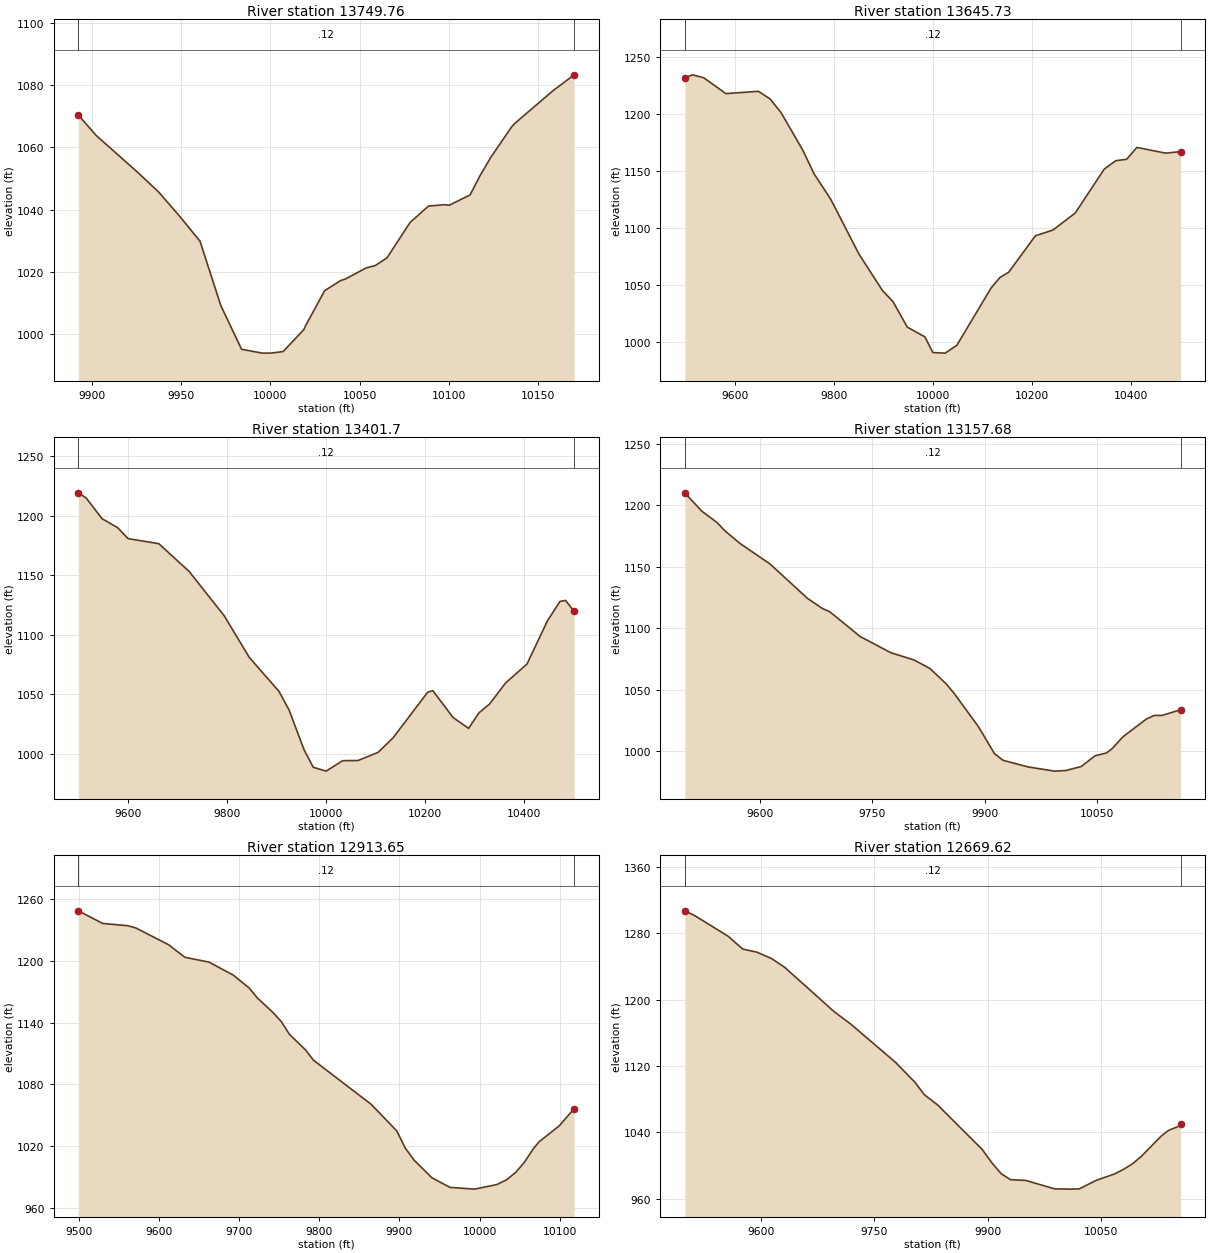
Type RM Length L Ch R = 1 ,13749.76,104.027300,104.027300,104.027300
XS GIS Cut Line= 2
561266.407184869794680.128830716 561505.12246266794537.984733507
#Sta/Elev= 30
9892.3491070.4019902.3731063.8289925.6271052.0049937.2651045.7419948.9041038.074
9960.5421029.9069972.1811009.2729983.819995.21989995.458993.9892 10000.1993.9935
 10007.1994.487610018.741001.57510019.651002.73110030.371014.03410039.191017.231
10042.011017.77910053.65 1021.3410058.741022.09910065.291024.55710078.281035.957
10088.571041.19210097.831041.62210100.211041.45310111.841044.75310117.381050.871
10123.481056.83310135.121066.56310136.921067.716 10158.41078.24810170.181083.304
#Mann= 3 , 0 , 0
9892.349    0.12       09892.349    0.12       010170.18    0.12       0
#XS Ineff= 2 , 0
       0                               0
Bank Sta=9892.349,10170.18
Exp/Cntr=0.3,0.1

Type RM Length L Ch R = 1 ,13645.73,244.028100,244.028100,244.028100
XS GIS Cut Line= 6
560990.872244823794951.435260021561300.128739904794796.190808523
561356.356716743 794759.75349997561558.612087565794608.650368678
561711.884301446794517.548074794561852.364139021 794445.56535674
#Sta/Elev= 30
9499.0611231.7939514.8981234.4079537.3171231.8419582.1561217.9319647.7621219.952
9671.2071213.3469693.6281201.2159737.8791167.9939760.1041147.6819793.8791125.319
9850.9491077.1779898.6141045.0979919.8041035.4119948.6821013.0819984.2381004.513
10000.31990.751610025.22990.2485 10048.7997.079510118.041047.42910135.771056.607
 10153.5 1061.2110207.511093.18710242.761098.19410288.051113.16710346.611151.696
10369.891159.06110391.881160.30610412.621170.70710470.54 1165.7110500.961167.011
#Mann= 3 , 0 , 0
9499.061    0.12       09499.061    0.12       010500.96    0.12       0
#XS Ineff= 2 , 0
       0                               0
Bank Sta=9499.061,10500.96
Exp/Cntr=0.3,0.1

Type RM Length L Ch R = 1 , 13401.7,244.028200,244.028200,244.028200
XS GIS Cut Line= 6
561030.051218639794964.020632919561379.780083181794884.216812333
561465.210873145794890.320932828561580.318588373794936.660167167
561695.988975015794937.907474506561990.750200505794831.454252892
#Sta/Elev= 30
9499.1651219.0439515.064 1214.71 9546.971197.3889578.7051189.7799599.6491180.632
9661.7571176.364 9723.181153.0149794.1081115.7539844.3931081.0349904.4581052.478
9924.679 1037.079955.4941003.1379973.851988.74299999.755985.538210033.17994.2848
10064.38994.465710104.761001.27310134.781013.38710205.191051.89610215.351053.026
10256.351030.47310287.631021.41510308.481034.43710329.861041.81110362.271059.466
10405.521075.39710446.841111.649 10472.2 1127.9410483.311128.73310500.811119.637
#Mann= 3 , 0 , 0
9499.165    0.12       09499.165    0.12       010500.81    0.12       0
#XS Ineff= 2 , 0
       0                               0
Bank Sta=9499.165,10500.81
Exp/Cntr=0.3,0.1

Type RM Length L Ch R = 1 ,13157.68,244.028200,244.028200,244.028200
XS GIS Cut Line= 6
560982.726699833795053.696271973561110.005119366795033.758087146
561241.591998402795046.534360895 561383.98847281795097.305751809
561530.143740696795179.227684337561609.778653003795198.086131815
#Sta/Elev= 30
9499.1311210.0129521.942 1195.079542.4251185.8069552.6671179.2179572.9441168.903
9613.1761152.191 9663.221124.2829683.2261116.0649693.2611113.3159733.7131093.296
9774.638 1080.199805.8031074.2429826.8761067.3949848.3551055.1059859.1721047.258
9891.6221020.2769913.298998.18479924.545 992.8399958.286987.40729993.571984.0105
 10008.4984.466410029.15987.721410047.63996.440510063.07998.776210070.331002.116
10085.11 1011.9210116.771026.49110127.13 1029.2410137.231029.20410162.181033.853
#Mann= 3 , 0 , 0
9499.131    0.12       09499.131    0.12       010162.18    0.12       0
#XS Ineff= 2 , 0
       0                               0
Bank Sta=9499.131,10162.18
Exp/Cntr=0.3,0.1

Type RM Length L Ch R = 1 ,12913.65,244.028200,244.028200,244.028200
XS GIS Cut Line= 6
560825.793507935795285.016161084560984.209547917795250.419468478
561122.035649424795254.528469696561231.199179894795286.886183399
561376.162927478795367.437178044561413.324287734795375.499373646
#Sta/Elev= 30
9499.1691248.785 9529.59 1236.519560.8341234.3189571.0811232.0899611.8671215.815
9632.085 1203.629662.4051198.8659692.476 1186.299712.476 1173.729722.4761164.217
9742.4891149.6219752.544 1141.049762.5991128.7829782.7081113.5689792.7631103.484
9864.705 1060.639896.6631034.7379907.3161018.0569918.1641006.4239940.499989.1993
9963.118979.80139993.841978.099510021.63982.521910033.43987.052210045.23994.3698
10056.38 1004.6110067.511017.74310074.391024.15210099.531039.67410118.141056.358
#Mann= 3 , 0 , 0
9499.169    0.12       09499.169    0.12       010118.14    0.12       0
#XS Ineff= 2 , 0
       0                               0
Bank Sta=9499.169,10118.14
Exp/Cntr=0.3,0.1

Type RM Length L Ch R = 1 ,12669.62,244.028100,244.028100,244.028100
XS GIS Cut Line= 6
560933.639553586795804.927930585561100.121477163795697.892077508
561300.833270672795543.895274052 561385.88972227795501.160062919
561404.624011543795481.536626509561449.933178796795412.179032357
#Sta/Elev= 30
9499.0671307.1569512.371 1301.299556.5761276.4249575.7911261.0319594.3461257.365
9613.7531249.7359631.4371238.9469697.0591185.3999718.7161170.6619778.1541124.405
9803.625 1100.66 9816.361085.3559833.4631073.4219892.7711019.5649905.5061003.525
9918.017990.22899930.426983.00939950.073982.19459988.968971.925810010.59971.6265
10021.36971.968610044.49982.451610067.87989.845210080.36995.677510092.13 1002.36
10103.911011.47410129.961035.71210139.721042.549   101521046.97310155.55 1049.88
#Mann= 3 , 0 , 0
9499.067    0.12       09499.067    0.12       010155.55    0.12       0
#XS Ineff= 2 , 0
       0                               0
Bank Sta=9499.067,10155.55
Exp/Cntr=0.3,0.1

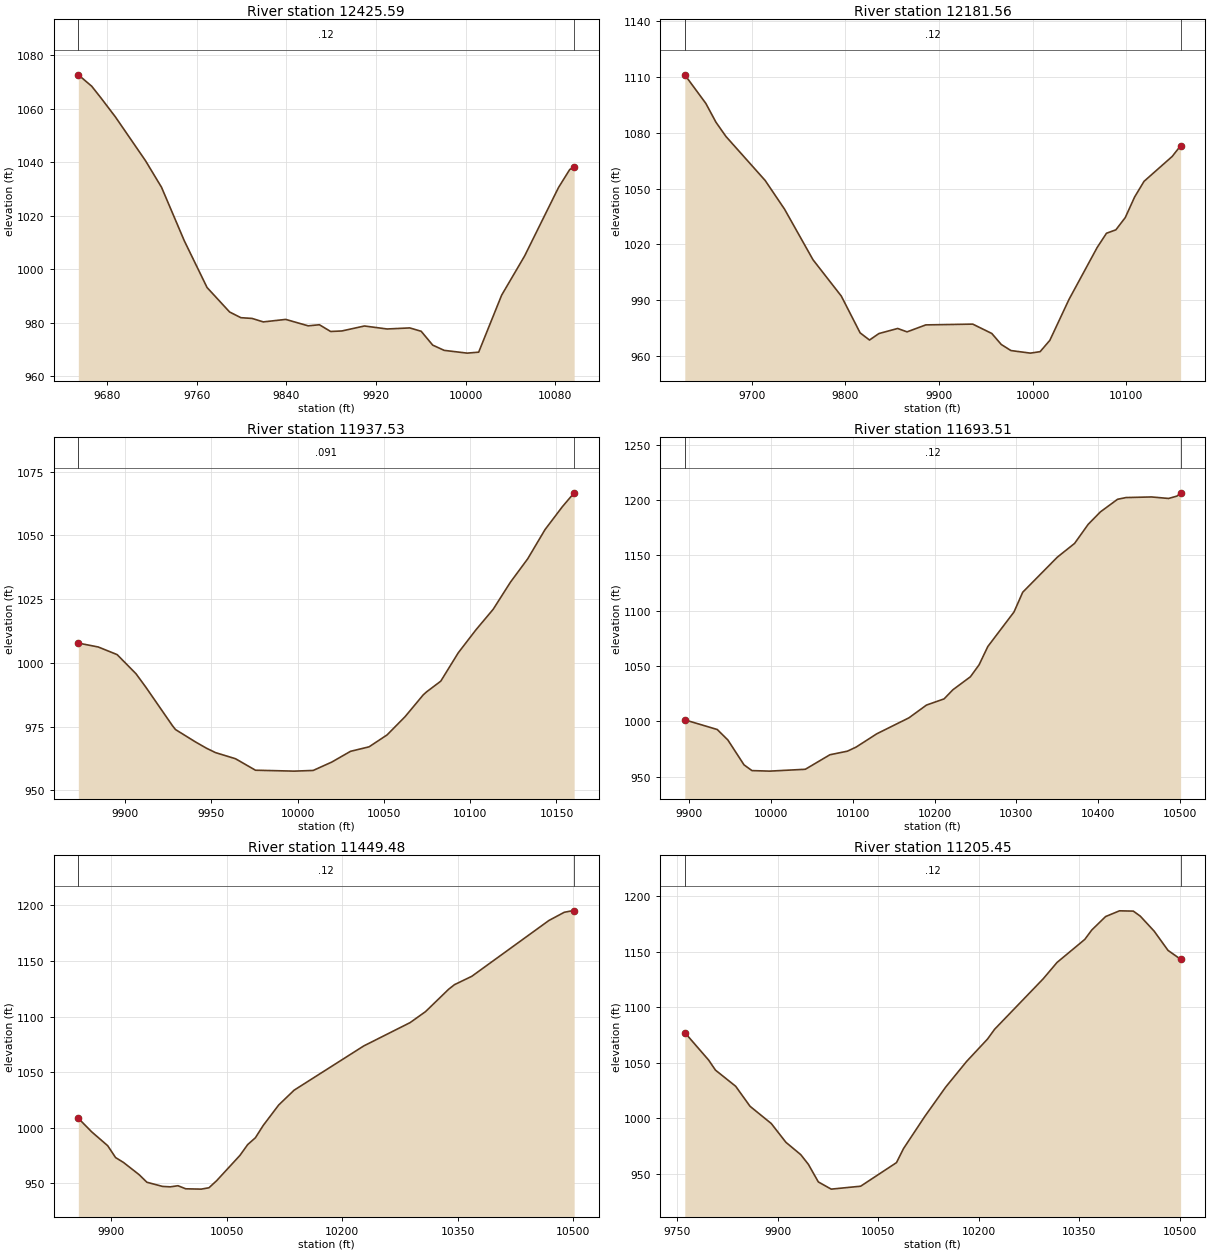
Type RM Length L Ch R = 1 ,12425.59,244.028200,244.028200,244.028200
XS GIS Cut Line= 6
561528.458377902795876.258322561561554.946999906795772.947395478
561560.282544651795703.444297248561557.163628269795635.726608193
561527.645230946795487.447252513561522.739427116795441.050924172
#Sta/Elev= 30
9654.3581072.6229666.2931068.3629674.3111064.1149687.4111056.8989714.3471040.475
9728.5941030.5719748.9511010.532 9769.21993.10189789.322983.95699799.377 981.823
9809.386981.54469819.395980.24649839.414981.18159859.435978.77749869.446979.1863
9879.456976.66419889.467 976.8579909.601978.71999929.834977.59999950.066 977.999
9960.261976.73619970.518971.57099980.775969.6032 10001.3968.573310011.55968.9386
10032.04990.2505 10052.51004.87110082.741030.46210092.78 1037.2210096.731038.145
#Mann= 3 , 0 , 0
9654.358    0.12       09654.358    0.12       010096.73    0.12       0
#XS Ineff= 2 , 0
       0                               0
Bank Sta=9654.358,10096.73
Exp/Cntr=0.3,0.1

Type RM Length L Ch R = 1 ,12181.56,244.028200,244.028200,244.028200
XS GIS Cut Line= 6
561707.964796027795895.024902646561730.807220822795843.610399384
561744.906544559795790.905020629561764.410164065795596.341145011
561789.829548191795484.059728778 561783.35918699795376.026724082
#Sta/Elev= 30
9628.2411111.1859650.7231095.8099661.5741085.6569672.3231077.9619714.1821054.314
9734.8851038.8799765.2811011.6749795.572992.09079815.689 972.3049825.722968.4417
9835.755971.9291 9855.82974.66429865.853972.84119885.918976.58999936.101977.0086
9956.462971.97429966.643966.02419976.942962.77539997.742961.393210008.14 962.187
10018.51968.273210038.94990.237310069.071018.21510079.071025.91410089.111027.751
10099.151034.34910109.191045.46510119.231053.85710149.341067.26210158.341073.029
#Mann= 3 , 0 , 0
9628.241    0.12       09628.241    0.12       010158.34    0.12       0
#XS Ineff= 2 , 0
       0                               0
Bank Sta=9628.241,10158.34
Exp/Cntr=0.3,0.1

Type RM Length L Ch R = 1 ,11937.53,244.028200,244.028200,244.028200
XS GIS Cut Line= 6
562016.880814417795546.168898031562002.774889314795509.743383685
561971.496240733795456.558675779561944.117378545795396.128754184
561928.509304153795330.747062945561928.334528445795278.168368597
#Sta/Elev= 30
9872.9531007.7819884.5081006.2529895.449 1003.269906.389 995.742 9912.14990.4206
9927.477975.39529929.244973.87429940.845969.00099947.203966.54459952.447964.8173
9964.048962.41259975.595957.90999998.103 957.55610009.03957.819610019.84961.1166
10030.65965.321410041.42967.088310051.86971.7695 10062.3978.927810072.74987.4243
10074.76988.658410082.95 992.842 10093.11003.97310103.261012.91310113.331021.044
10123.341031.68210133.35 1040.8610143.36 1052.2910153.391061.25910160.251066.728
#Mann= 3 , 0 , 0
9872.953   0.091       09872.953   0.091       010160.25   0.091       0
#XS Ineff= 2 , 0
       0                               0
Bank Sta=9872.953,10160.25
Exp/Cntr=0.3,0.1

Type RM Length L Ch R = 1 ,11693.51,244.028100,244.028100,244.028100
XS GIS Cut Line= 6
562062.811422313795543.719989279562082.516217178795527.240204515
562113.110926934795511.679090438562230.902624158795473.746328818
562462.485339578795384.283358722562629.228656359795332.930111581
#Sta/Elev= 30
9894.419 1001.329934.113992.57649947.107983.10569966.901960.57229976.594955.4016
9998.364954.926810041.85956.598810071.97969.744310093.34972.970910104.09976.7127
10129.27988.688710168.581003.13210190.081014.68510211.581020.26810222.331028.495
10243.791040.27410254.451051.13410265.121067.66410297.131098.895 10307.81116.762
10350.171148.51610371.23 1160.9110387.891178.19410402.831189.45610423.771200.835
10434.171202.41510465.371202.95410486.171201.59510496.571203.74710500.961206.691
#Mann= 3 , 0 , 0
9894.419    0.12       09894.419    0.12       010500.96    0.12       0
#XS Ineff= 2 , 0
       0                               0
Bank Sta=9894.419,10500.96
Exp/Cntr=0.3,0.1

Type RM Length L Ch R = 1 ,11449.48,244.028200,244.028200,244.028200
XS GIS Cut Line= 6
562028.374975929 795767.84865215 562089.21457367795751.966295155
562139.920336844795744.261036534562353.890417372795721.530645832
562512.543518833 795709.59490427 562667.80669516795703.501104585
#Sta/Elev= 30
 9857.091008.5689874.547996.27959895.222983.89529905.468 973.2179915.714968.8238
9935.999957.86029946.114951.01639966.343947.27089976.436946.87539986.506947.8757
9996.577945.110910016.69944.820310026.74946.0466 10036.8952.481210066.96975.1677
10077.02984.885910087.07991.069210097.121002.04210117.231020.46810137.341033.846
10227.72 1073.6310287.891094.60510307.951104.49110338.031124.671 10345.61128.778
10368.071136.28710468.151186.47610488.161193.88910498.171195.18810500.981194.592
#Mann= 3 , 0 , 0
 9857.09    0.12       0 9857.09    0.12       010500.98    0.12       0
#XS Ineff= 2 , 0
       0                               0
Bank Sta=9857.09,10500.98
Exp/Cntr=0.3,0.1

Type RM Length L Ch R = 1 ,11205.45,97.627000,97.627000,97.627000
XS GIS Cut Line= 6
 561999.70079234795895.932380718562074.514724325 795907.82650583
562119.845878578795922.113139529562218.970247012 795971.61856222
562330.691080133796013.029981403562703.164441157796114.960868522
#Sta/Elev= 30
9761.3171077.141  9796.91052.4069807.0961043.3799837.1891028.9089858.6671010.874
9890.348995.37619912.194978.4965 9934.31967.42139945.666958.73299960.533942.8951
9979.735936.437210023.64939.054710077.07960.239310087.64972.923210119.281001.718
10150.511028.15310181.741051.21710212.981071.36310223.39 1080.0510295.931125.432
10316.621140.17310358.011160.86910368.361169.27210389.06 1181.4110409.75 1186.56
10430.451186.30110440.791181.77610461.491168.30210482.181151.00910500.981143.031
#Mann= 3 , 0 , 0
9761.317    0.12       09761.317    0.12       010500.98    0.12       0
#XS Ineff= 2 , 0
       0                               0
Bank Sta=9761.317,10500.98
Exp/Cntr=0.3,0.1