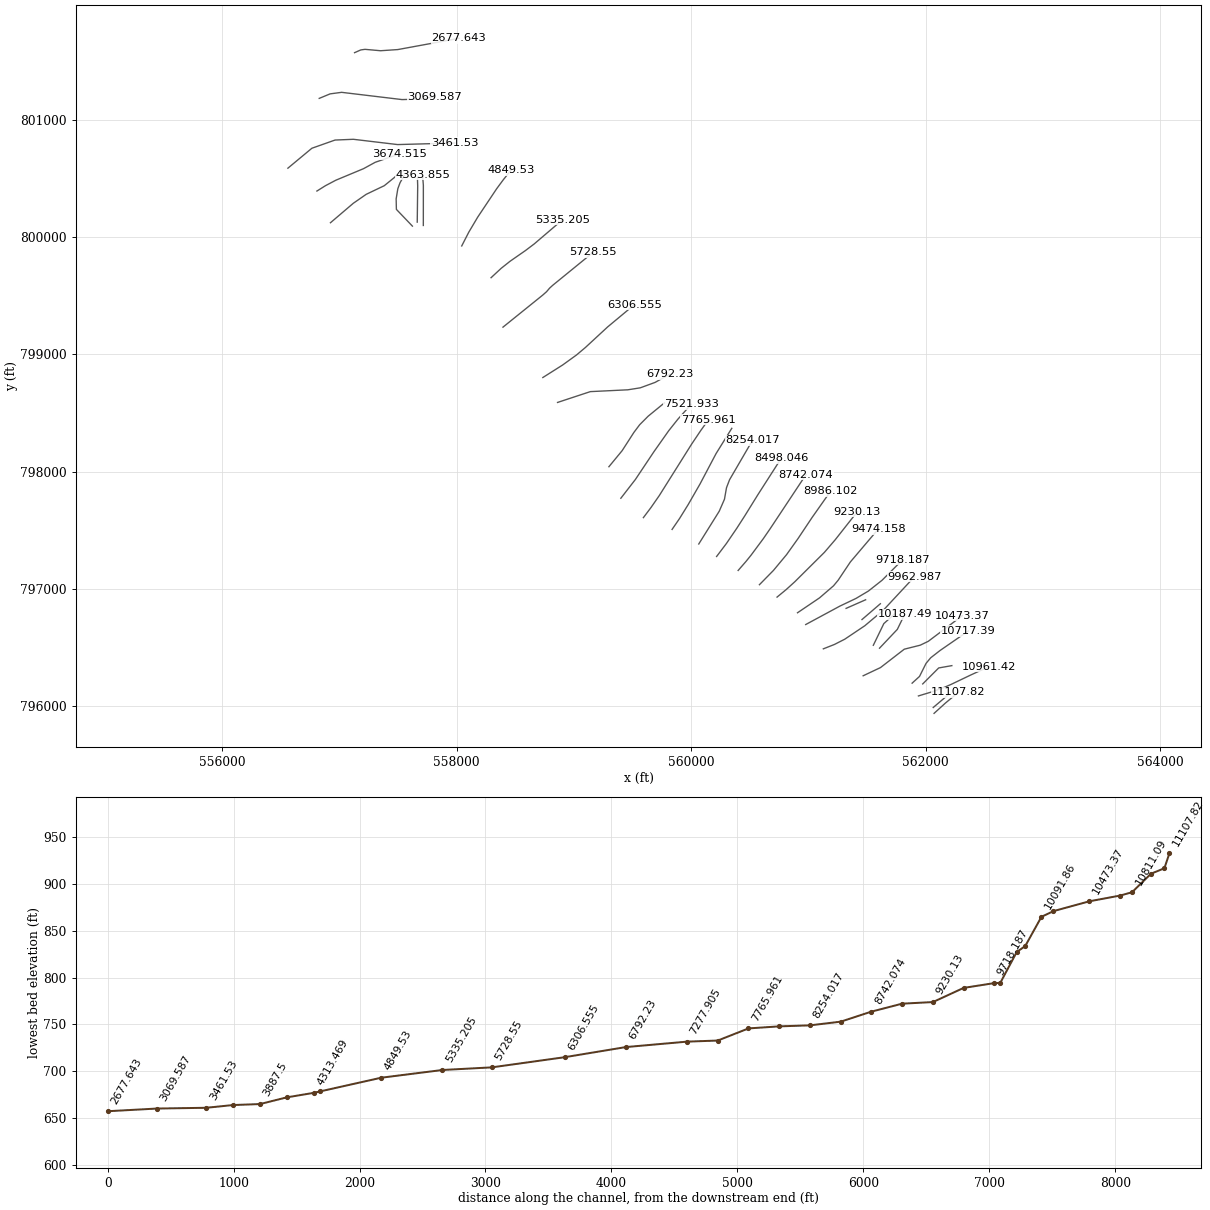
HEC-RAS study 10956_ras.prj: 10956

--- 10956_ras.g01 (geometry) --- (continued)

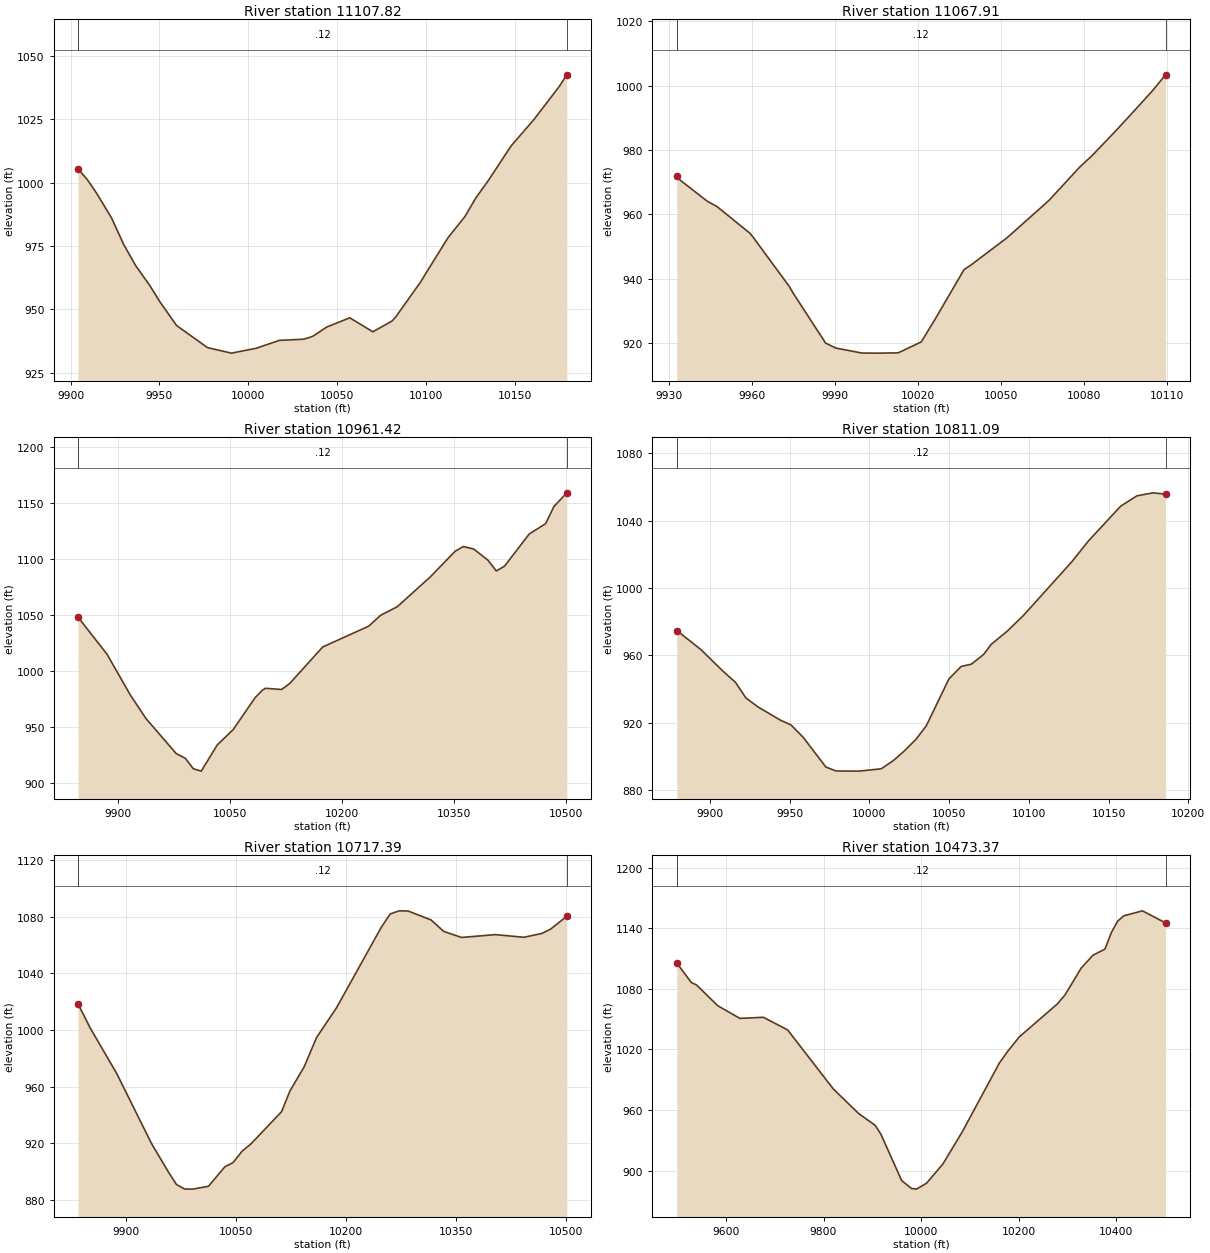
Type RM Length L Ch R = 1 ,11107.82,39.908000,39.908000,39.908000
XS GIS Cut Line= 3
562071.007742047795937.733566061562169.075907439796026.629888669
562279.138021141796117.642790362
#Sta/Elev= 30
9904.1541005.3839909.5421001.0469914.973995.42769923.039 986.0579929.863975.6216
9936.536967.32559944.752959.22399950.033953.20279959.642943.62729977.027934.8992
9990.524932.712310004.31934.597910017.52937.739110031.02   938.210034.09938.7898
10036.52939.4255 10044.2942.998910057.18946.643610070.16941.130110081.03945.4161
10083.13947.075310096.73960.476610112.42978.213510122.06986.649910128.11993.9274
10135.041000.67910148.011014.48910160.991025.00210175.19 1038.0110179.331042.503
#Mann= 3 , 0 , 0
9904.154    0.12       09904.154    0.12       010179.33    0.12       0
#XS Ineff= 2 , 0
       0                10058.61       0
Bank Sta=9904.154,10179.33
Exp/Cntr=0.3,0.1

Type RM Length L Ch R = 1 ,11067.91,106.493200,106.493200,106.493200
XS GIS Cut Line= 2
562063.952478349795987.825938329562198.708014965796102.121210247
#Sta/Elev= 27
9932.885971.83349934.259 970.5399943.976964.03289947.371962.45549959.436954.0545
9960.484952.89689973.596937.55049974.896935.58989986.709919.95939990.356918.4212
9999.821916.869410005.82916.839510012.93 916.91810021.28920.327110026.05927.0503
10036.74942.795110039.16944.1854 10052.2 952.64810052.27952.696410065.38962.7256
10067.65964.5211 10078.5974.630610083.11978.326210091.61  985.9810098.57992.4731
10104.72998.284610109.581003.368
#Mann= 3 , 0 , 0
9932.885    0.12       09932.885    0.12       010109.58    0.12       0
#XS Ineff= 2 , 0
       0                               0
Bank Sta=9932.885,10109.58
Exp/Cntr=0.3,0.1

Type RM Length L Ch R = 1 ,10961.42,150.331400,150.331400,150.331400
XS GIS Cut Line= 6
561937.846081704796086.459745495562054.057222593796121.729882021
562162.435045579796161.308644049562218.907888118796186.026603957
562385.858187172796265.843082723 562540.72461637796336.814055308
#Sta/Elev= 30
9847.1081048.4589885.9361015.3739917.287978.79999938.188957.84869978.468926.6875
9990.738922.425410001.35913.141610012.01910.983210033.34934.315810054.67948.0092
10083.94976.446110093.14982.858910097.65984.906410119.48983.8782 10130.4 989.242
 10174.51021.81710235.941040.36910252.091050.15910274.261057.769 10318.6 1084.51
10351.691107.31110362.691111.49910376.61  1109.210395.691099.16610406.691089.659
10417.691093.94710450.691122.64510472.691131.89310483.691147.10110500.981159.411
#Mann= 3 , 0 , 0
9847.108    0.12       09847.108    0.12       010500.98    0.12       0
#XS Ineff= 2 , 0
       0                               0
Bank Sta=9847.108,10500.98
Exp/Cntr=0.3,0.1

Type RM Length L Ch R = 1 ,10811.09,93.696800,93.696800,93.696800
XS GIS Cut Line= 3
561974.350629359 796188.90095371562110.517218769796325.067543104
562222.695911527 796344.82228145
#Sta/Elev= 30
9879.264974.79229894.324963.53979908.466950.44269916.173943.92349922.608 934.735
9930.315929.32879944.458921.42359950.893918.6901  9958.6911.27759972.742893.6939
9979.177891.30799993.319891.232210007.46892.603510015.17897.5642 10021.6902.8941
10029.31910.185410035.75918.195310049.89945.972210057.59953.428910064.03954.7972
10071.74960.623510076.38966.529510086.54974.444510096.69983.780610127.151015.829
10137.311027.91510157.621048.68210167.771054.80910177.921056.59810185.741055.795
#Mann= 3 , 0 , 0
9879.264    0.12       09879.264    0.12       010185.74    0.12       0
#XS Ineff= 2 , 0
       0                               0
Bank Sta=9879.264,10185.74
Exp/Cntr=0.3,0.1

Type RM Length L Ch R = 1 ,10717.39,244.028200,244.028200,244.028200
XS GIS Cut Line= 6
561883.967902012796195.304552996561947.091946204796252.836382963
562002.893856742796364.290863735 562042.19589085796411.503360387
562121.711568193796473.541103797562363.114325537796640.315671552
#Sta/Elev= 30
9834.3731018.569 9850.86 1001.659887.364969.16989934.485920.06259957.859 899.631
9968.751 890.9379979.643 887.8059990.536887.702710012.37889.728710034.54903.4294
10045.88906.459210058.19914.515510070.49919.774310112.02942.397910123.38956.9792
10142.98974.227510159.59994.6357 10186.71015.54710247.971072.57510260.121081.958
10272.281084.18110284.431084.06310315.631077.80510333.231069.62110357.361065.388
 10403.61067.38610442.441065.51410466.751068.183 10478.91071.27310500.921080.341
#Mann= 3 , 0 , 0
9834.373    0.12       09834.373    0.12       010500.92    0.12       0
#XS Ineff= 2 , 0
       0                               0
Bank Sta=9834.373,10500.92
Exp/Cntr=0.3,0.1

Type RM Length L Ch R = 1 ,10473.37,285.877900,285.877900,285.877900
XS GIS Cut Line= 6
561466.470313733796258.348776483561614.391852039796328.271332656
561817.234727275 796485.09788761561952.623985137796519.043981458
562021.506198834 796552.02315666562312.367191862796771.259617649
#Sta/Elev= 30
 9499.161105.5859529.2851086.2389539.8451083.8329583.3351063.2619628.7061050.734
9676.6771051.8469726.4851039.3069820.086980.80569871.905956.5211  9905.9944.7898
9917.512936.09639960.077890.13459980.405882.19059990.569881.588610010.93887.3884
10044.53906.423410084.28938.270410160.21 1006.3810176.611017.633   102011032.312
10279.041065.00210295.321074.24110327.891100.45710352.221113.37310376.741119.376
10390.231136.141 10402.9 1147.1710415.571152.40710453.581157.31310500.931145.368
#Mann= 3 , 0 , 0
 9499.16    0.12       0 9499.16    0.12       010500.93    0.12       0
#XS Ineff= 2 , 0
       0                               0
Bank Sta=9499.16,10500.93
Exp/Cntr=0.3,0.1

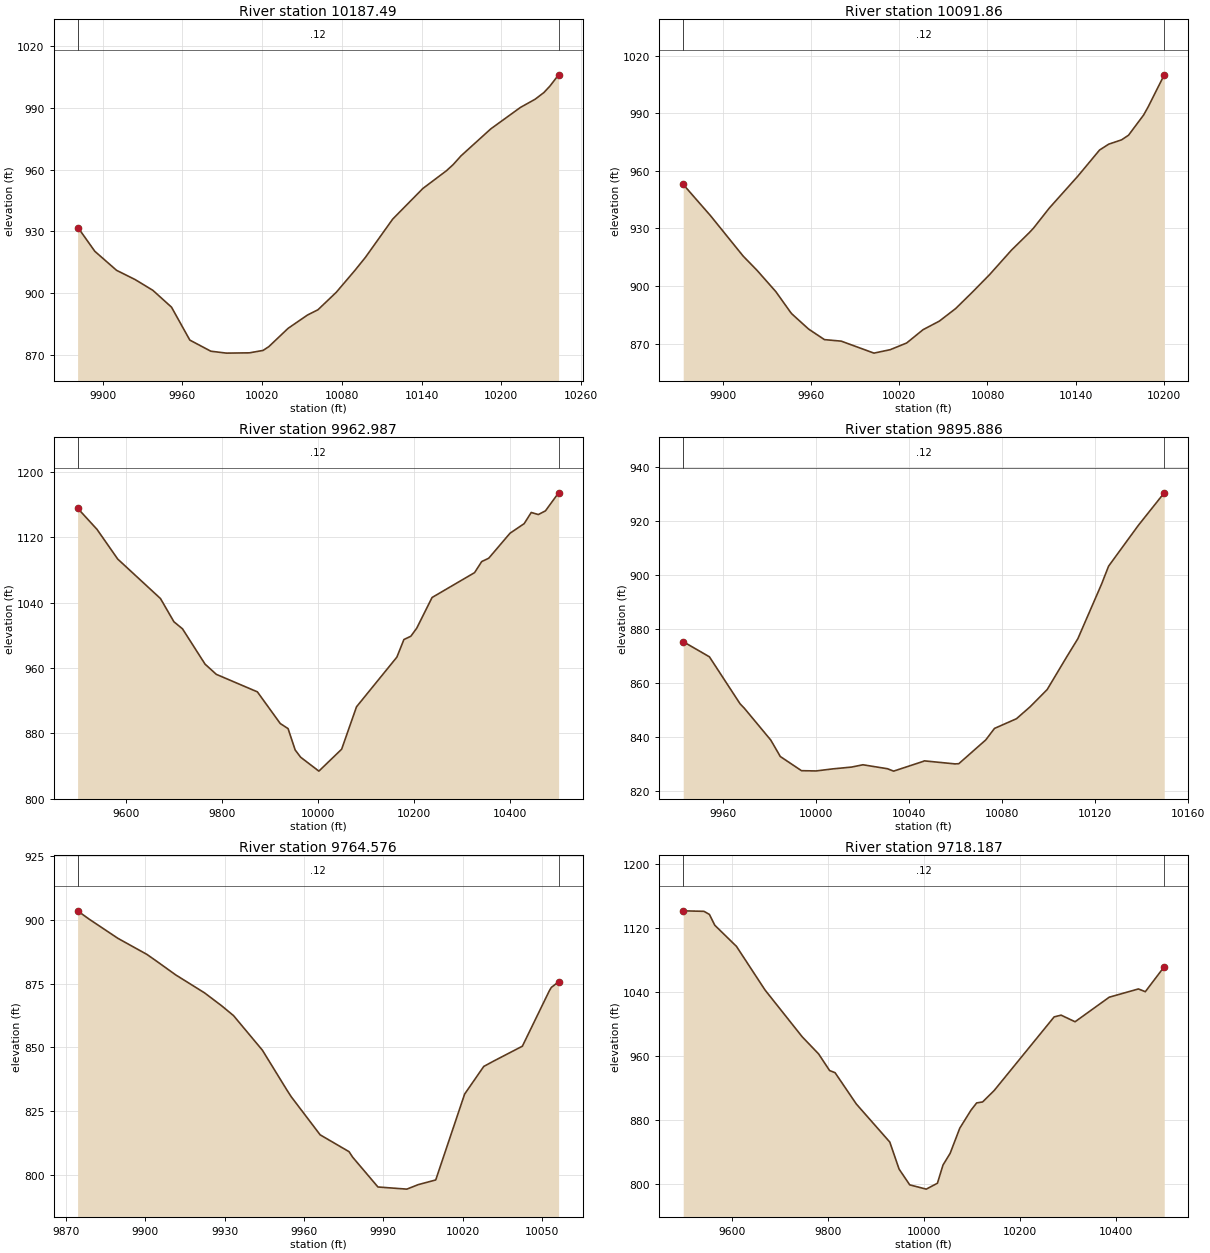
Type RM Length L Ch R = 1 ,10187.49,95.626100,95.626100,95.626100
XS GIS Cut Line= 3
561606.065864354796493.688345477561757.754033834796653.842831418
561819.840354383796780.837577999
#Sta/Elev= 30
9881.206931.74019883.013930.51249894.198920.3664 9910.56911.16019924.333 906.753
9937.825901.4948 9951.88893.32279965.653877.38679981.451871.9973  9993.2871.0648
10010.54871.205910020.75872.372510025.08874.195310039.62883.078210054.16889.5054
10062.07892.064710075.84900.522310089.61910.932110097.79 917.45410118.29935.9639
10141.06950.842910158.74959.393710163.83962.390610169.87 966.70710192.13979.6824
10214.39990.053310225.52994.050910232.13997.303610236.651000.43210243.151005.858
#Mann= 3 , 0 , 0
9881.206    0.12       09881.206    0.12       010243.15    0.12       0
#XS Ineff= 2 , 0
       0                               0
Bank Sta=9881.206,10243.15
Exp/Cntr=0.3,0.1

Type RM Length L Ch R = 1 ,10091.86,128.873700,128.873700,128.873700
XS GIS Cut Line= 3
561553.151386595796518.381768426561642.753235584796703.229677311
561733.060610896796784.365209824
#Sta/Elev= 30
  9873.3952.90049891.768936.68629913.993915.5926 9923.39 908.1929936.219 897.038
9946.316886.17239947.332885.28689958.445877.55169969.241872.03299980.671871.2292
 10002.9864.989410014.01866.802310025.12870.281710036.24877.208310047.35881.6862
10058.46 888.26610069.57 896.63210081.37 905.84310096.33918.676910108.63927.9433
10111.29930.147810122.07940.642110141.22957.069810156.18970.8555 10162.4973.9131
10171.15976.165410175.84978.558810186.11989.113310189.29993.495610200.12 1010.05
#Mann= 3 , 0 , 0
  9873.3    0.12       0  9873.3    0.12       010200.12    0.12       0
#XS Ineff= 2 , 0
       0                               0
Bank Sta=9873.3,10200.12
Exp/Cntr=0.3,0.1

Type RM Length L Ch R = 1 ,9962.987,67.101600,67.101600,67.101600
XS GIS Cut Line= 6
561127.043173784796488.109244142561221.545495956796525.345249257
561309.779871455796570.335516765561480.720368827796685.058525395
561639.243508674796818.187520668 561903.61754472797102.200907736
#Sta/Elev= 30
9499.055 1155.519539.5331129.5439582.643 1093.229671.6741044.9119699.7271016.457
9717.5961007.8299764.555964.63439788.035952.13149873.523930.72329921.198891.9714
9937.486885.72149952.263859.61839963.623850.753410001.62833.714310049.07860.5476
10080.01912.4252 10164.1973.239110178.79994.776610193.18998.778110205.551008.724
10237.431046.20110325.951076.61110340.71 1090.1110355.461094.27510399.721124.814
10429.231136.56310443.981150.23710458.741147.69910473.491152.17410500.961174.271
#Mann= 3 , 0 , 0
9499.055    0.12       09499.055    0.12       010500.96    0.12       0
#XS Ineff= 2 , 0
       0                               0
Bank Sta=9499.055,10500.96
Exp/Cntr=0.3,0.1

Type RM Length L Ch R = 1 ,9895.886,131.309800,131.309800,131.309800
XS GIS Cut Line= 2
561456.494273931796737.800469428561613.121128023796872.556006059
#Sta/Elev= 30
9943.081875.4123 9954.12869.90789954.301869.83179967.493852.39239969.452850.6103
9980.685838.92959984.785832.83439993.877827.587210000.12827.487810007.07828.2291
10015.45 828.93210020.26 829.77910030.78828.313410033.45827.421810046.12831.0188
10046.64831.226910059.84830.101510061.45830.178410073.03838.992810076.78843.2555
10086.22846.846610092.11851.295110099.41857.659710107.45869.2756 10112.6876.5303
10122.78896.770710125.79903.407510138.11917.989610138.99918.9879 10149.7930.5971
#Mann= 3 , 0 , 0
9943.081    0.12       09943.081    0.12       0 10149.7    0.12       0
#XS Ineff= 2 , 0
       0                10023.94       0
Bank Sta=9943.081,10149.7
Exp/Cntr=0.3,0.1

Type RM Length L Ch R = 1 ,9764.576,46.389500,46.389500,46.389500
XS GIS Cut Line= 2
561321.033210933796833.046529338 561487.53743425796906.421271801
#Sta/Elev= 27
 9874.34903.56999878.675900.32619879.184899.97539889.603892.76229900.531886.4841
9903.982883.98349911.459878.41789922.386871.3507 9928.78 866.3339933.314862.4503
9944.242 848.8639953.578833.1167 9955.17830.56199966.098815.63059977.026809.0188
9978.376806.87079987.954795.15549998.882794.318410003.17796.072410009.81797.9221
10020.74831.624710027.97842.472910031.67844.555510042.59850.433310052.77872.1492
10053.52873.473410056.29875.7266
#Mann= 3 , 0 , 0
 9874.34    0.12       0 9874.34    0.12       010056.29    0.12       0
#XS Ineff= 2 , 0
       0                               0
Bank Sta=9874.34,10056.29
Exp/Cntr=0.3,0.1

Type RM Length L Ch R = 1 ,9718.187,244.028200,244.028200,244.028200
XS GIS Cut Line= 6
560976.612329794796695.169969997561267.640344465796852.167936259
561404.919696845796917.604796912  561511.2029147796980.802177864
561626.992608892797072.226966298561802.538298895797247.076662627
#Sta/Elev= 30
9499.0451142.0189542.2611141.3939553.5191137.5519564.7771124.0069609.9431097.565
 9669.481043.017 9746.86984.5655 9781.09963.13449803.909942.39779815.319939.6991
9859.564900.58529929.285853.00579948.674819.1678 9970.83799.504410005.21794.1906
10028.47801.5713 10040.1824.314810054.95838.8902   10075870.314610098.26892.7239
10110.18901.929610122.56903.153310146.49917.299410271.651009.49810286.161011.621
10315.18 1003.37 10386.3 1034.0610447.151044.38810461.471040.94310500.92 1072.17
#Mann= 3 , 0 , 0
9499.045    0.12       09499.045    0.12       010500.92    0.12       0
#XS Ineff= 2 , 0
       0                               0
Bank Sta=9499.045,10500.92
Exp/Cntr=0.3,0.1

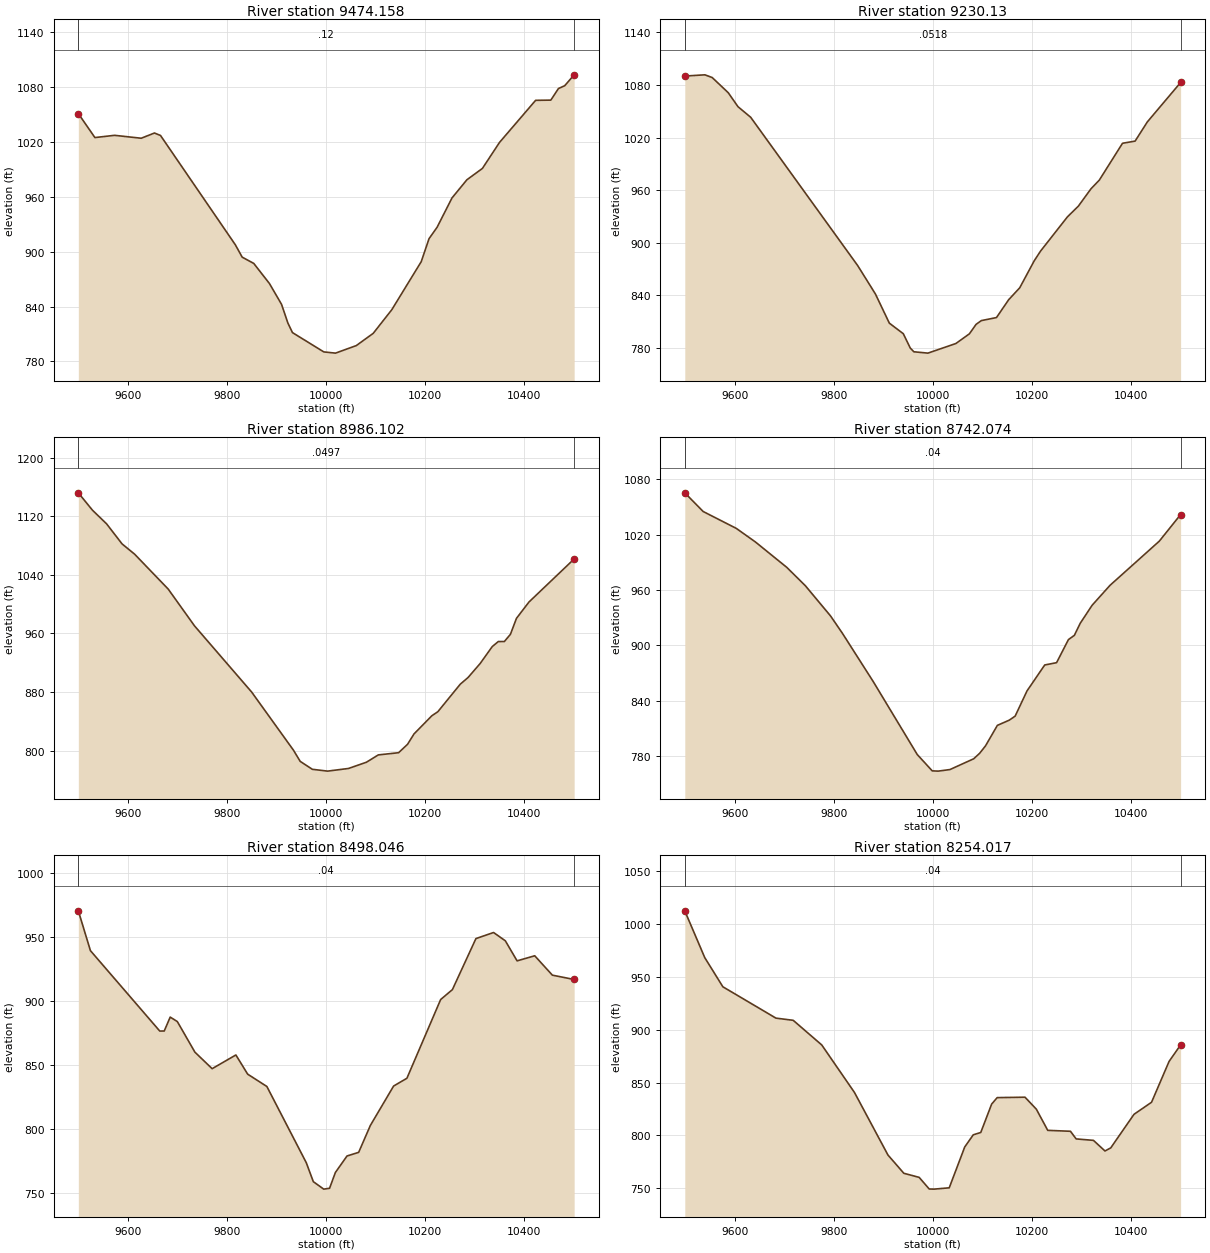
Type RM Length L Ch R = 1 ,9474.158,244.028200,244.028200,244.028200
XS GIS Cut Line= 6
 560906.74778867796795.647887326561094.983451789796922.985492652
561213.759035288797025.437150355 561253.12281294797072.857144595
561357.192056507797228.592976185561595.687121528797509.481303076
#Sta/Elev= 30
9499.0881051.1869532.5751024.9139572.3911027.3729626.2211024.178 9652.871029.901
9665.1321027.2259816.456907.51769830.185 894.0669853.567887.22779885.251865.2207
9909.712 842.4579922.498822.01999931.785811.51289995.096790.394710018.73789.0655
10060.75797.306310094.97810.718610132.48836.561610191.97889.1438 10207.7914.2674
10223.97926.715110254.17958.880910284.27978.760410315.61991.162410350.141019.602
10423.121065.65710453.84 1065.88 10469.21078.54610481.891081.65910500.971093.565
#Mann= 3 , 0 , 0
9499.088    0.12       09499.088    0.12       010500.97    0.12       0
#XS Ineff= 2 , 0
       0                               0
Bank Sta=9499.088,10500.97
Exp/Cntr=0.3,0.1

Type RM Length L Ch R = 1 , 9230.13,244.028200,244.028200,244.028200
XS GIS Cut Line= 6
560732.248427373796929.134417889560810.024539317 796993.27666472
560883.560025866797059.951565142561135.987150517 797310.63254465
561228.166442957797418.044880073  561416.6860923797657.224968828
#Sta/Elev= 30
9499.0381090.1979539.6921091.6159554.4531088.5029586.8431071.1889606.5681055.213
9632.1921043.1579848.291873.95819884.237841.43589912.405808.12849940.573796.0898
9954.657779.73569961.898775.4698  9990.3773.923210046.91 784.91510074.17795.9678
 10087.6806.736810098.33 811.05610128.89814.530410153.47834.865210175.83848.4862
10205.29879.475510218.03890.458510272.09929.361310294.42941.778710319.89961.5364
10336.71971.451110383.551013.47910409.02 1015.9610433.641037.79610500.981082.869
#Mann= 3 , 0 , 0
9499.038  0.0518       09499.038  0.0518       010500.98  0.0518       0
#XS Ineff= 2 , 0
       0                               0
Bank Sta=9499.038,10500.98
Exp/Cntr=0.3,0.1

Type RM Length L Ch R = 1 ,8986.102,244.028100,244.028100,244.028100
XS GIS Cut Line= 6
560582.014523286797034.927076817560701.169025288797156.252444924
560813.614280771797291.579225478560910.945821046797428.025094548
561031.253705557797608.400159124561187.560419984797830.304493203
#Sta/Elev= 30
9499.0561151.9129527.681 1128.179556.2011109.5819587.4051082.245  9612.71068.287
9680.7361020.552 9733.74970.47719849.326880.08649933.855800.7182 9947.46785.5046
9971.993774.716110002.75772.230810045.16775.883810081.22784.373310105.26794.3658
 10146.2797.357310164.22808.751110177.39  822.9810213.45847.792310225.47853.2207
10270.79890.799310286.55899.922810311.02919.031410335.48942.162210347.71949.0084
10359.94949.064210372.18958.847110384.41980.673110409.711002.96610500.981061.688
#Mann= 3 , 0 , 0
9499.056  0.0497       09499.056  0.0497       010500.98  0.0497       0
#XS Ineff= 2 , 0
       0                               0
Bank Sta=9499.056,10500.98
Exp/Cntr=0.3,0.1

Type RM Length L Ch R = 1 ,8742.074,244.028200,244.028200,244.028200
XS GIS Cut Line= 6
560400.613362401797156.386254689560466.795801115797232.436276444
560510.353133937 797286.30682945560615.272846884797427.586709292
  560677.0937179797517.744218339560979.012164215797973.358668707
#Sta/Elev= 30
9499.0191065.1879536.1671044.9489603.1311026.6559641.711 1011.979705.232984.3885
 9742.61964.5884 9793.47931.87659817.222913.28659879.987860.58289968.809781.6712
    9999764.023210010.98763.719110034.91765.426510082.79777.078110094.76782.9735
10106.73791.097210130.67813.275110154.61818.907610166.58823.283510190.51850.5328
10223.59876.537510226.42878.704810250.36881.2126 10274.3906.213210286.27910.8088
10298.24923.978910322.24943.445210358.39965.019210457.951012.852   105011041.667
#Mann= 3 , 0 , 0
9499.019    0.04       09499.019    0.04       0   10501    0.04       0
#XS Ineff= 2 , 0
       0                               0
Bank Sta=9499.019,10501
Exp/Cntr=0.3,0.1

Type RM Length L Ch R = 1 ,8498.046,244.028200,244.028200,244.028200
XS GIS Cut Line= 6
560216.872162924797275.495397969560299.536866705797384.864522077
560388.552274602797515.446702323560456.630582597797621.309647115
560571.463937172797806.542835277560767.548140639798112.054684074
#Sta/Elev= 30
9499.031970.10679523.481939.03839663.579876.32279672.598876.3548  9684.7887.2061
9699.087883.71549734.595859.87399769.417846.9593 9817.41857.66449841.189842.7064
9880.035833.07129959.654773.63559973.907758.82069994.942753.007410006.72753.6714
10018.48765.987710042.02778.862610065.55   781.710089.08802.626710136.15833.4271
10163.03839.497710231.19900.891410254.96908.650510302.49948.447710338.14953.1954
 10361.9946.726410385.67931.076210421.31935.043810456.96919.917910500.99916.5381
#Mann= 3 , 0 , 0
9499.031    0.04       09499.031    0.04       010500.99    0.04       0
#XS Ineff= 2 , 0
       0                               0
Bank Sta=9499.031,10500.99
Exp/Cntr=0.3,0.1

Type RM Length L Ch R = 1 ,8254.017,244.028200,244.028200,244.028200
XS GIS Cut Line= 6
560064.800684782797382.159733118560239.343122467797661.564697598
560283.999338788797763.962924379 560301.21159991797861.786057296
560327.305950044797929.853184208560522.094374134798264.730258287
#Sta/Elev= 30
9499.1291012.7199539.401968.43419576.017940.76849683.252911.06599718.169908.9896
9775.879885.63129841.978840.60559909.606781.37469941.731764.05549972.657760.1945
9992.986749.159710003.03749.054610033.42750.309710064.75789.014210081.95800.5018
10097.16802.737410119.09 829.61210130.31835.751610186.52836.141810209.48824.7583
10232.45804.742810278.37803.863410289.86796.631810324.81795.252810348.11785.1919
10359.77788.150410406.71819.928210442.16831.3427 10477.6870.029410500.92885.7256
#Mann= 3 , 0 , 0
9499.129    0.04       09499.129    0.04       010500.92    0.04       0
#XS Ineff= 2 , 0
       0                               0
Bank Sta=9499.129,10500.92
Exp/Cntr=0.3,0.1

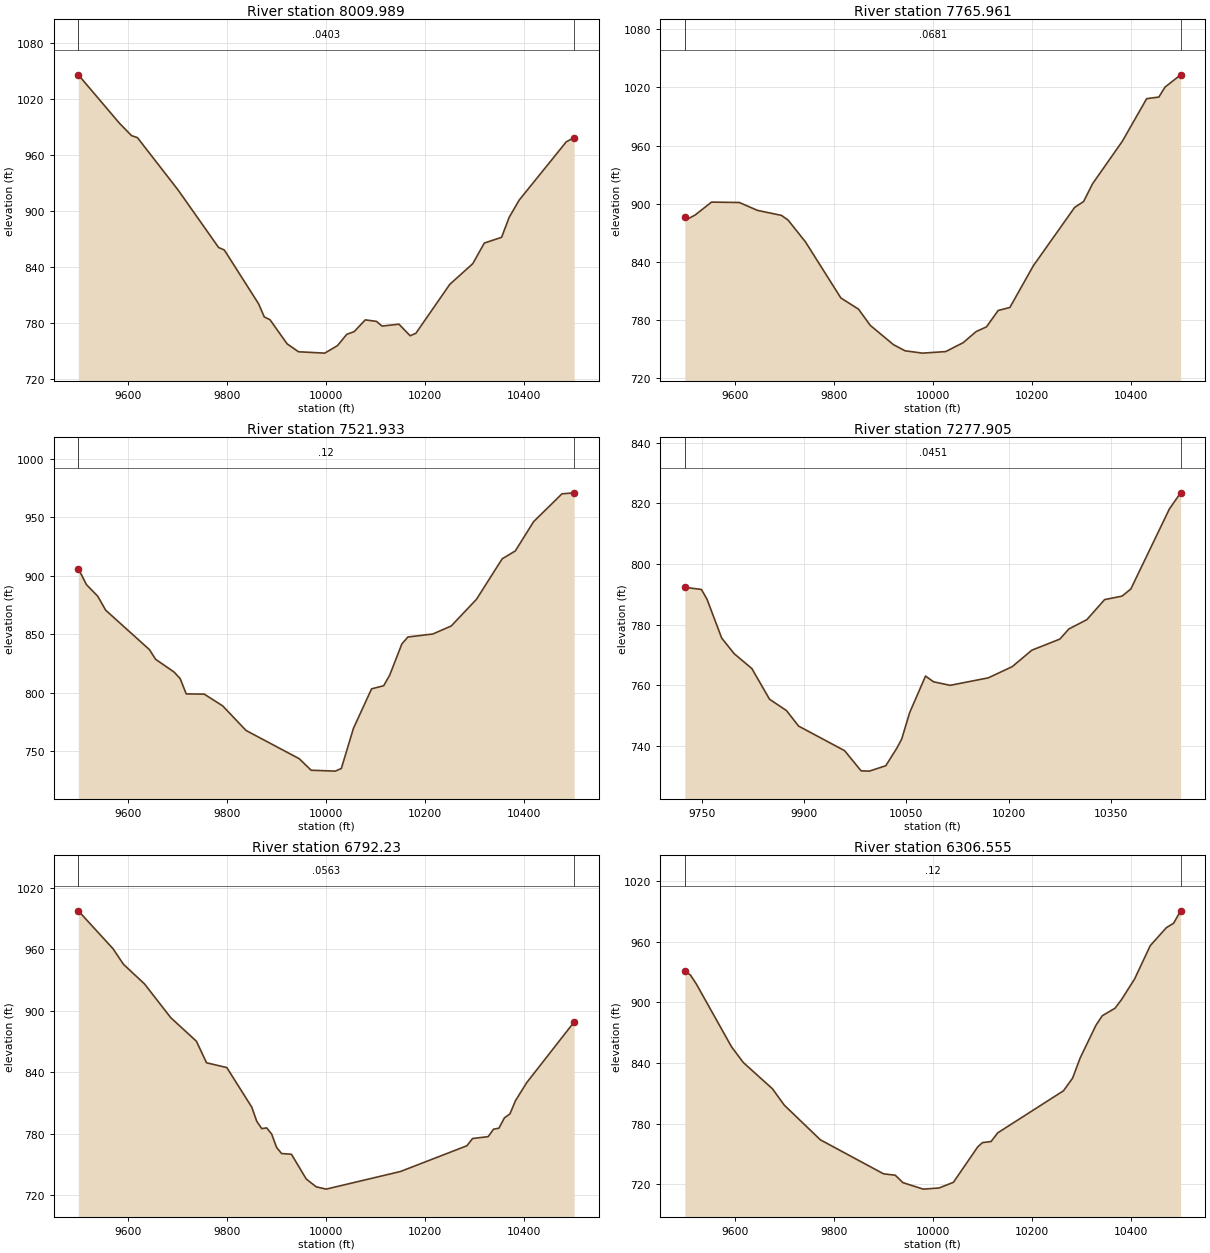
Type RM Length L Ch R = 1 ,8009.989,244.028100,244.028100,244.028100
XS GIS Cut Line= 6
559837.209805886797506.291882032559901.245530015797599.830585458
559974.712031203797718.463009275560075.625061496797894.027048665
560212.592576793798153.513847474560346.266116247798368.371768411
#Sta/Elev= 30
9499.0321046.3949582.298994.38649606.536981.2228 9618.47979.03789700.806922.7832
9782.537861.22989794.071858.55829863.276800.9098 9874.81786.79289886.345783.7951
9920.947757.93229944.016749.44679997.051747.981310022.82756.079710041.39768.1341
10056.46771.022510078.88783.640810101.39782.040610112.79 776.97910146.99779.0389
10169.56766.593410181.18769.287210249.61821.701810296.14843.941710319.41 866.008
 10354.3872.1398 10369.6893.533610389.82912.026310485.05974.554410500.97979.0553
#Mann= 3 , 0 , 0
9499.032  0.0403       09499.032  0.0403       010500.97  0.0403       0
#XS Ineff= 2 , 0
       0                               0
Bank Sta=9499.032,10500.97
Exp/Cntr=0.3,0.1

Type RM Length L Ch R = 1 ,7765.961,244.028200,244.028200,244.028200
XS GIS Cut Line= 6
559592.529528143797606.860851599559657.972889507797693.858231857
559728.640400721797795.721882986560003.197350016798232.629405808
560083.381196646798352.045418981560147.231366647798440.690333598
#Sta/Elev= 30
 9499.02886.01989503.129883.78749519.764888.27449553.034901.65469609.273 901.246
9645.786893.12899694.469887.9361 9707.93882.99779742.915860.54699814.402802.7279
9850.146791.13419873.784774.46779920.718754.50469944.185748.19869979.385745.7861
10026.29747.386810061.46 756.55610087.87  768.0810108.57772.847610132.26789.7899
10155.95  792.9210203.33835.943310286.89896.230710304.95902.254610323.03920.5908
10383.25964.485610432.351008.395   104571010.06510469.331020.25110500.991033.012
#Mann= 3 , 0 , 0
 9499.02  0.0681       0 9499.02  0.0681       010500.99  0.0681       0
#XS Ineff= 2 , 0
       0                               0
Bank Sta=9499.02,10500.99
Exp/Cntr=0.3,0.1

Type RM Length L Ch R = 1 ,7521.933,244.028200,244.028200,244.028200
XS GIS Cut Line= 6
559400.376105425797772.221857162559524.871483535797932.837666252
559682.373110605 798168.91210056559809.007539426798348.458670411
559886.833439399798446.326632188560000.119896959798573.192946646
#Sta/Elev= 30
9499.025906.21749515.411892.4881 9538.36 882.4669554.335870.54929642.812 836.788
9655.244828.54239692.537817.63919704.906811.95829717.048798.93549753.472798.7387
9790.667788.69869837.949767.62879945.547743.43919969.458733.602610018.27732.8405
10030.49735.113810054.93769.4475 10091.6803.253810116.04805.938810128.26815.0055
 10152.7841.625810164.92847.607610215.44850.207810252.49857.0472 10303.6879.9094
10355.54914.556810381.99 921.25910419.16946.413510476.32970.168110500.95971.0173
#Mann= 3 , 0 , 0
9499.025    0.12       09499.025    0.12       010500.95    0.12       0
#XS Ineff= 2 , 0
       0                               0
Bank Sta=9499.025,10500.95
Exp/Cntr=0.3,0.1

Type RM Length L Ch R = 1 ,7277.905,485.675100,485.675100,485.675100
XS GIS Cut Line= 6
559298.596734956798040.952486046 559411.59441589 798178.15263529
559511.523456677798333.249477567559560.960126477798399.102727832
559633.458594545798471.907108739559771.984505652798585.309883781
#Sta/Elev= 30
9725.411792.3108 9749.77791.61139757.939788.40889779.475775.57949797.749770.4259
9823.715765.50769849.606755.39119874.489751.64069892.211746.53159959.693738.4096
9983.771731.76749995.809731.669310020.01733.452810036.15  739.2310043.31 742.258
10054.95750.954810078.25 763.04310089.99 761.14710114.33759.978110170.26762.4462
10205.34 766.14310234.03771.568610275.09775.228710288.29778.569410314.69781.6487
10340.67788.256510366.29 789.418 10379.1791.749810435.61818.150810452.11823.4929
#Mann= 3 , 0 , 0
9725.411  0.0451       09725.411  0.0451       010452.11  0.0451       0
#XS Ineff= 2 , 0
       0                               0
Bank Sta=9725.411,10452.11
Exp/Cntr=0.3,0.1

Type RM Length L Ch R = 1 , 6792.23,485.675000,485.675000,485.675000
XS GIS Cut Line= 6
558860.528095052798588.984157576559140.171608419798681.271827686
 559460.08115826798696.807893113 559566.15565008798713.714948477
559692.821845239798760.111859315559817.954325122798830.143552808
#Sta/Elev= 30
9499.073997.57959569.099960.6176 9590.37945.31779632.893926.16839685.752893.2895
9737.656870.2658 9758.15849.20959799.069844.55669849.559805.8532 9859.59792.0685
9869.622784.94939879.653785.64439889.665779.64749899.665766.60849909.666760.6285
9929.667759.88249959.668735.67599979.669728.12219999.698725.861410149.96743.0686
 10284.1768.1967 10295.6775.266410327.16777.117110338.03784.4009 10348.9785.3486
10359.85795.372310371.12799.328810382.38812.283410404.91829.764710500.87889.1061
#Mann= 3 , 0 , 0
9499.073  0.0563       09499.073  0.0563       010500.87  0.0563       0
#XS Ineff= 2 , 0
       0                               0
Bank Sta=9499.073,10500.87
Exp/Cntr=0.3,0.1

Type RM Length L Ch R = 1 ,6306.555,578.004300,578.004300,578.004300
XS GIS Cut Line= 6
 558735.15928022798801.509592088 558904.24829183798908.475422004
559022.573614879798993.951300055559098.983300427799058.370068318
559287.998945324799233.166888595559517.462225117799423.976182392
#Sta/Elev= 30
9499.044931.39919510.689926.86649522.522918.04579593.519855.95189617.185840.4905
 9676.35814.31529700.041798.21649773.044763.86369900.617730.20779924.323728.8194
9939.837 721.4749980.835715.045110012.88 716.17910041.84721.794310091.06756.9219
10100.44761.076410117.93762.196110131.36770.749810264.21812.398610282.61824.8936
10298.05844.979410329.66877.0786 10342.6886.709610368.46894.1884 10381.4902.6363
   10408923.145610439.53956.068710471.93973.840410486.83978.338110500.99990.6214
#Mann= 3 , 0 , 0
9499.044    0.12       09499.044    0.12       010500.99    0.12       0
#XS Ineff= 2 , 0
       0                               0
Bank Sta=9499.044,10500.99
Exp/Cntr=0.3,0.1

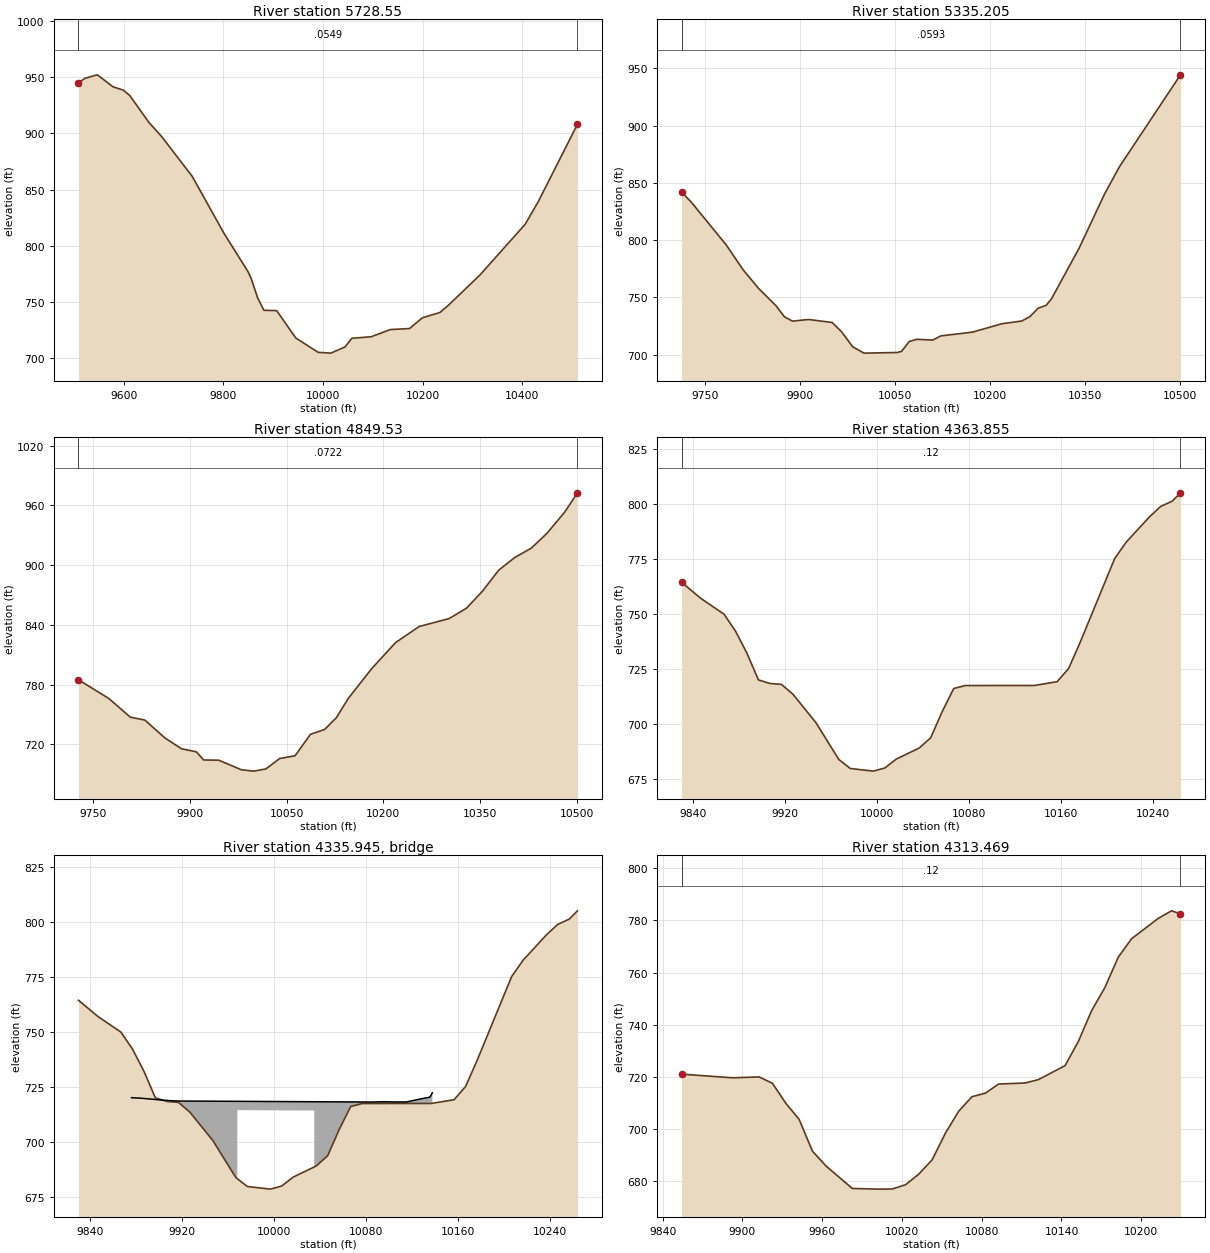
Type RM Length L Ch R = 1 , 5728.55,393.345800,393.345800,393.345800
XS GIS Cut Line= 6
558395.267878856799231.109281335558733.797025926799504.053397836
558766.978579105799533.443297378558792.933951299799563.784980838
558820.102343267799588.509286964559165.852412005799870.317307943
#Sta/Elev= 30
9509.127 944.9329521.688949.04279546.913952.23599578.546 941.5589599.132938.6187
9612.039933.81249650.761909.73489676.576896.98759737.397861.8099 9801.43810.8996
9849.455776.88879855.887770.78999868.693753.64039881.471742.37619907.111742.0889
9945.596717.64849990.388 704.91810015.94704.197910044.57709.756710058.09717.4427
10096.93718.796910135.43725.202410173.92726.107310199.58735.645110234.94740.4363
 10250.9746.410310315.19  773.7910406.08819.023910432.04838.906710511.05908.1439
#Mann= 3 , 0 , 0
9509.127  0.0549       09509.127  0.0549       010511.05  0.0549       0
#XS Ineff= 2 , 0
       0                               0
Bank Sta=9509.127,10511.05
Exp/Cntr=0.3,0.1

Type RM Length L Ch R = 1 ,5335.205,485.675000,485.675000,485.675000
XS GIS Cut Line= 6
558293.740574879799652.660005924558379.406961924799732.197377251
558455.696131712799792.865878104558587.443949171799884.541571027
558661.736755561799940.743656207 558905.15672229800148.570315606
#Sta/Elev= 30
9712.814841.99269728.619832.92579783.402795.83699810.335773.96449834.239758.0498
9862.436742.53079875.212733.17359887.989729.31439913.542730.72199950.805728.1338
9965.692719.99819983.079706.9763   10001701.380510053.29701.916910060.45702.8873
 10072.6711.583210084.75 713.46510109.73 712.78810122.27716.400410172.42719.7022
10218.91727.033210250.28729.416710262.99733.125710275.97740.492610288.96743.1773
10297.33748.8555 10341.1793.213510381.01840.186910404.61864.060210500.98944.2596
#Mann= 3 , 0 , 0
9712.814  0.0593       09712.814  0.0593       010500.98  0.0593       0
#XS Ineff= 2 , 0
       0                               0
Bank Sta=9712.814,10500.98
Exp/Cntr=0.3,0.1

Type RM Length L Ch R = 1 , 4849.53,485.675100,485.675100,485.675100
XS GIS Cut Line= 6
558043.547607573799923.511108149558103.762209813800040.760759374
558179.410045615800168.559323014558342.898097363800413.348466692
558398.623744105800488.542763513558464.692311661800570.638320826
#Sta/Elev= 30
9727.288784.84139773.929766.27089807.654747.34439830.137744.43249861.612726.3007
9886.939715.61719909.913 712.5449921.427704.32349944.858704.08599980.004694.4624
 9999.22693.124810017.82695.323610039.25705.789110063.16708.569810087.08730.1455
10108.99734.976610127.22 746.82710145.46766.000110181.93796.055210219.02822.2441
10255.44838.349210302.01846.380910328.96856.769210353.85873.953710378.74894.8824
10403.89907.743710429.56917.156510453.62931.910110480.91953.045910500.98972.6526
#Mann= 3 , 0 , 0
9727.288  0.0722       09727.288  0.0722       010500.98  0.0722       0
#XS Ineff= 2 , 0
       0                               0
Bank Sta=9727.288,10500.98
Exp/Cntr=0.3,0.1

Type RM Length L Ch R = 1 ,4363.855,50.385300,50.385300,50.385300
XS GIS Cut Line= 3
557716.102405624800098.034290319557716.448818968800439.251466309
557709.320606427800532.134478589
#Sta/Elev= 30
9829.581764.36189846.546756.97959866.546749.87639876.546  742.219886.546732.0994
9896.546719.96969906.546718.34389916.546717.93449926.546713.48089946.546700.5693
9966.546683.77099976.546679.68539996.546678.485510006.55 679.90610016.55683.9695
10036.55689.001310046.55693.687510056.55 705.57510066.55716.038210076.55717.4063
10136.55717.426710156.55719.143510166.55725.125710176.56736.953110206.65775.1112
10216.68   782.610236.74793.984310246.77798.8611 10256.8  801.2510263.95805.0299
#Mann= 3 , 0 , 0
9829.581    0.12       09829.581    0.12       010263.95    0.12       0
#XS Ineff= 2 , 0
       0                               0
Bank Sta=9829.581,10263.95
Exp/Cntr=0.3,0.1

Type RM Length L Ch R = 3 ,4335.945,,,
BEGIN DESCRIPTION:
END DESCRIPTION:
Bridge Culvert--1,0,-1,-1, 0
Deck Dist Width WeirC Skew NumUp NumDn MinLoCord MaxHiCord MaxSubmerge Is_Ogee
14.692650,21.000000,2.6,0, 24, 24, , , 0.95, 0, 0,0,,
 9875.80 9883.89 9892.25 9894.07 9904.25 9913.98 9914.41 9917.23 9967.83 9967.83
10034.8310034.8310081.4710081.9210084.4910094.6010094.7610105.0310107.8710115.24
10125.4210125.6510135.5010137.63
  720.06  719.82  719.45  719.36  718.89  718.60  718.59  718.54  718.41  718.41
  718.22  718.22  718.10  718.10  718.09  718.22  718.22  718.13  718.13  718.13
  719.29  719.32  720.31  722.26
 -279.94 -280.18 -280.55 -280.64 -281.11 -281.40 -281.41 -281.46 -281.59  714.41
  714.22 -281.78 -281.90 -281.90 -281.91 -281.78 -281.78 -281.87 -281.87 -281.87
 -280.71 -280.68 -279.69 -277.74
 9875.80 9883.89 9892.25 9894.07 9904.25 9913.98 9914.41 9917.23 9964.28 9964.28
10031.2810031.2810081.4710081.9210084.4910094.6010094.7610105.0310107.8710115.24
10125.4210125.6510135.5010137.63
  720.06  719.82  719.45  719.36  718.89  718.60  718.59  718.54  718.41  718.41
  718.23  718.23  718.10  718.10  718.09  718.22  718.22  718.13  718.13  718.13
  719.29  719.32  720.31  722.26
 -279.94 -280.18 -280.55 -280.64 -281.11 -281.40 -281.41 -281.46 -281.59  714.41
  714.23 -281.77 -281.90 -281.90 -281.91 -281.78 -281.78 -281.87 -281.87 -281.87
 -280.71 -280.68 -279.69 -277.74
BR Coef=-1 , 0 , 0 ,, 0 ,,,0.8,0,1,0,
WSPro=,,,, 1 ,,,, 0 ,,,, 0 ,,,,-1 ,-1 ,-1 , 0 , 0 , 0 , 0 , 0
BC Design=,, 0 ,, 0 ,,,,,,

Type RM Length L Ch R = 1 ,4313.469,212.984800,212.984800,212.984800
XS GIS Cut Line= 3
557664.192426652800126.559074259557668.095699787800434.917652524
557665.917828649800501.752534158
#Sta/Elev= 30
9854.246721.0572 9892.69719.66399912.692719.98929922.692717.51819932.693709.8803
9942.694 703.7279952.695691.55419962.696685.92999982.697 677.215 10002.7676.9577
 10012.7677.0162 10022.7 678.626 10032.7682.7081 10042.7688.1725 10052.7 698.411
 10062.7706.8364 10072.7 712.41510082.71713.748410092.71 717.26410112.71717.6668
10122.71718.971710142.71724.322510152.71733.599110162.71745.435110172.72754.3434
10182.72765.917710192.73772.989110212.74780.782910222.74783.6985 10229.5782.5637
#Mann= 3 , 0 , 0
9854.246    0.12       09854.246    0.12       0 10229.5    0.12       0
#XS Ineff= 2 , 0
       0                               0
Bank Sta=9854.246,10229.5
Exp/Cntr=0.3,0.1

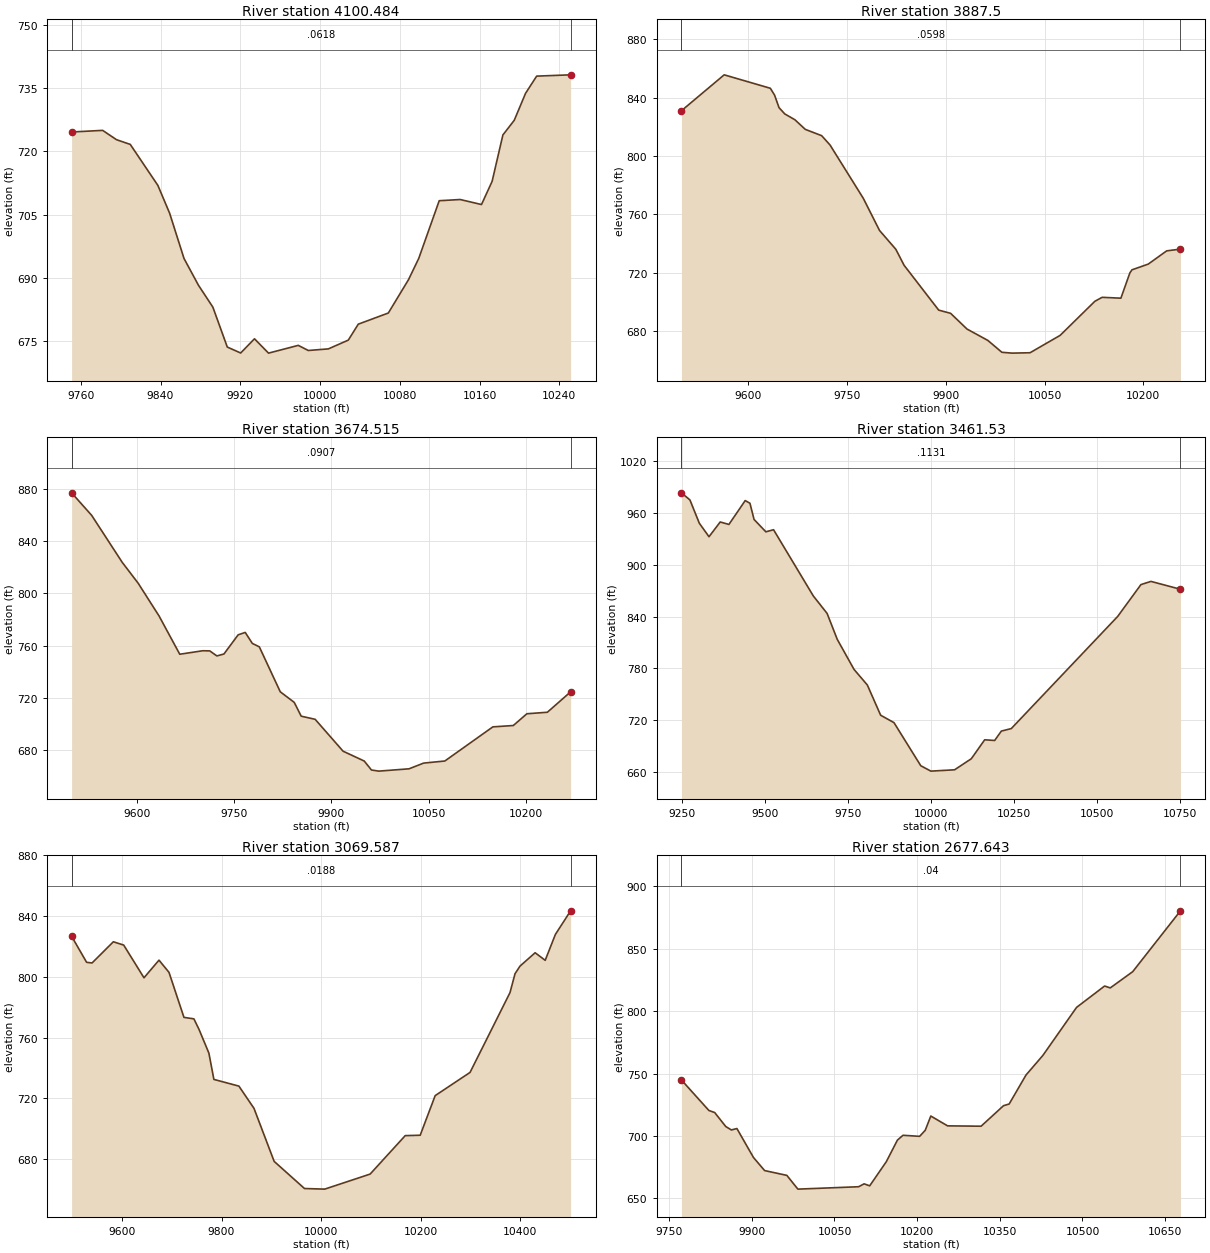
Type RM Length L Ch R = 1 ,4100.484,212.984800,212.984800,212.984800
XS GIS Cut Line= 6
 557622.98250252800092.497134715557486.401212787 800235.17929916
557484.349426513800324.495379724557498.708327345 800411.55423091
557517.691864041800462.749166574 557552.44867464800523.996792818
#Sta/Elev= 30
9750.781724.61579781.931725.00049795.775722.79639809.618721.67159837.304711.9494
9849.093705.35469863.554694.59929878.016688.26619892.477683.06589906.939673.5995
9920.362672.18849934.205675.55899948.297672.15819978.147673.99729988.172672.7858
10008.32673.162510028.33675.246310038.34 679.02710068.48681.675210088.75689.5996
10099.01694.641110119.52 708.31210140.58708.599910161.92707.407610172.58712.9081
 10183.4723.917810194.77 727.38810206.14733.800510217.26  737.8710251.33738.1786
#Mann= 3 , 0 , 0
9750.781  0.0618       09750.781  0.0618       010251.33  0.0618       0
#XS Ineff= 2 , 0
       0                               0
Bank Sta=9750.781,10251.33
Exp/Cntr=0.3,0.1

Type RM Length L Ch R = 1 ,  3887.5,212.984700,212.984700,212.984700
XS GIS Cut Line= 6
556924.194237702800121.194999738557118.931648136800287.171531132
557229.258118936800363.783728583557383.013018625800437.112102282
557468.325565636800506.307399476557530.048484364800566.251697219
#Sta/Elev= 30
9499.056 831.101  9563.9855.69849633.962846.47659640.399841.75929647.114833.2082
9655.795828.91689671.191824.91989686.978 818.3239711.799 814.008 9724.54 807.605
9774.901771.15339799.632749.04039824.363736.14749836.915725.17999889.389694.4664
9907.487692.26099932.393681.48649963.905673.72159985.311665.5574   10001664.9908
10028.01665.249510073.72677.167210126.39700.520910137.44703.236510165.86702.6388
10179.53719.986210182.71722.074610207.41 726.00210235.29735.056810256.27736.2698
#Mann= 3 , 0 , 0
9499.056  0.0598       09499.056  0.0598       010256.27  0.0598       0
#XS Ineff= 2 , 0
       0                               0
Bank Sta=9499.056,10256.27
Exp/Cntr=0.3,0.1

Type RM Length L Ch R = 1 ,3674.515,212.984800,212.984800,212.984800
XS GIS Cut Line= 6
556808.747009654800391.598069529556882.446772982800437.637342024
556970.358263127800484.047035581557206.205921559800582.348680363
557306.169661386800636.912369037557508.755291678 800706.82293072
#Sta/Elev= 30
9499.074876.87789530.029859.64149577.192823.69739601.743807.76979634.091782.6244
9666.003753.39679701.405756.04959712.349755.94979723.292752.06949734.236753.5925
9756.122768.24429767.066 770.0779778.009761.66519788.809759.04829821.129724.6621
9842.676716.5572 9853.45706.00299874.997703.60089918.091 679.2119950.735671.6857
9961.877664.83349973.097663.960410019.88665.731710042.43670.103710075.12671.6958
10149.29697.8274 10180.8698.8475 10201.8707.8468 10233.4709.0042 10269.3724.6124
#Mann= 3 , 0 , 0
9499.074  0.0907       09499.074  0.0907       0 10269.3  0.0907       0
#XS Ineff= 2 , 0
       0                               0
Bank Sta=9499.074,10269.3
Exp/Cntr=0.3,0.1

Type RM Length L Ch R = 1 , 3461.53,391.943500,391.943500,391.943500
XS GIS Cut Line= 6
556561.317537054800586.594782431556765.995958194800756.626823869
556963.219408977800826.390424507557119.773089967800832.860339311
557496.633520543800787.845642447557983.764689972800801.118906132
#Sta/Elev= 30
 9249.08983.48619274.656975.22759302.931 948.2119331.998932.6201 9365.75949.7042
9391.941946.85919440.965974.51169455.214971.40789467.635952.62149503.087938.3135
9526.264940.73369646.072863.91979687.378843.80549718.025813.69579768.511778.8832
9808.605 760.7649848.619725.79219888.659717.24139969.364667.28039999.874661.0261
10071.09662.552910121.54675.401110161.72697.329810191.78 696.545 10211.8707.4028
10241.83710.334810561.93840.217810631.99 877.14410662.04880.864110750.97871.7525
#Mann= 3 , 0 , 0
 9249.08  0.1131       0 9249.08  0.1131       010750.97  0.1131       0
#XS Ineff= 2 , 0
       0                               0
Bank Sta=9249.08,10750.97
Exp/Cntr=0.3,0.1

Type RM Length L Ch R = 1 ,3069.587,391.943500,391.943500,391.943500
XS GIS Cut Line= 6
556828.517888345801181.743612682556921.305648634801220.162430013
557019.540179824801233.272588022557534.414724413801171.481459627
557692.105725287801175.591525323557814.960851397801196.445839618
#Sta/Elev= 30
9499.064826.70829529.175809.57389540.112809.14329582.826823.09619603.659820.9235
9644.349799.3912 9674.48 810.9919694.568802.97919724.588773.31999744.588772.3346
9754.601765.58319774.675749.79239784.711732.4641 9834.93728.05129865.241713.3965
9905.712678.47939966.626 660.61210007.22660.212710098.38670.114410168.86695.4443
10198.93695.700310228.98721.781210299.01737.066210379.18789.586710389.28802.0421
10399.38807.103610429.68815.868710449.89810.884410470.32827.924510500.93843.4791
#Mann= 3 , 0 , 0
9499.064  0.0188       09499.064  0.0188       010500.93  0.0188       0
#XS Ineff= 2 , 0
       0                               0
Bank Sta=9499.064,10500.93
Exp/Cntr=0.3,0.1

Type RM Length L Ch R = 1 ,2677.643,567.086200,567.086200,567.086200
XS GIS Cut Line= 6
557129.807893238801571.512408758557182.882362989801594.903624405
557218.694531209 801599.88224601557351.661338825801588.005387953
557498.231685609801597.932252939558019.996851103801693.713609925
#Sta/Elev= 30
9772.293744.8122 9822.07720.3913 9832.59718.74039852.783707.47279862.879704.7867
 9872.92 705.8999902.969682.70949923.201672.21369963.577668.34859983.598657.3351
10093.78659.252810103.82661.575710113.87659.963110144.01679.293910164.19696.6052
10174.29700.499210204.58 699.65710214.68704.506610224.78715.921210255.21708.0605
10316.08707.772310356.78724.230110366.97 725.55710397.55748.802210428.13764.4939
10489.29803.008510540.25820.154810550.44818.623310591.21831.660310677.85880.4267
#Mann= 3 , 0 , 0
9772.293    0.04       09772.293    0.04       010677.85    0.04       0
#XS Ineff= 2 , 0
       0                               0
Bank Sta=9772.293,10677.85
Exp/Cntr=0.3,0.1