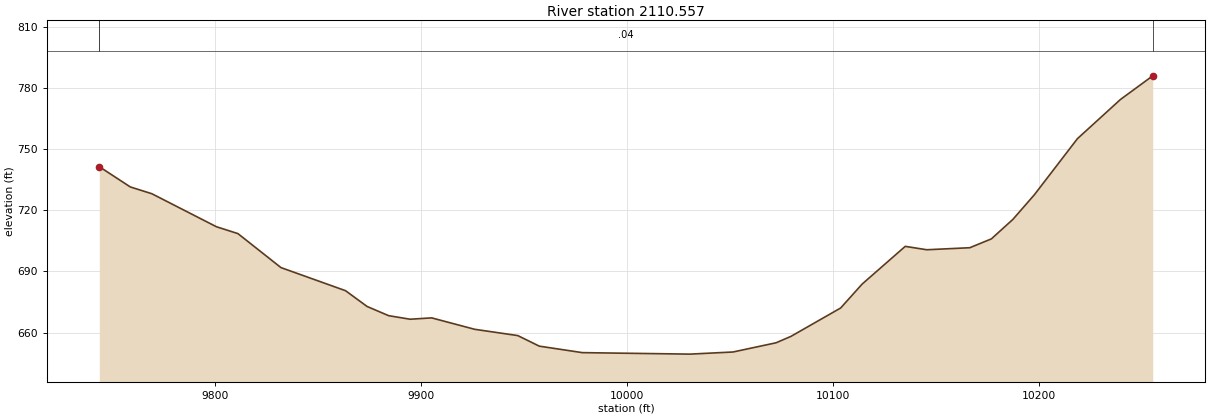
HEC-RAS study 10956_ras.prj: 10956

--- 10956_ras.g01 (geometry) --- (continued)

Type RM Length L Ch R = 1 ,2110.557,0.000000,0.000000,0.000000
XS GIS Cut Line= 2
556987.738840669801640.615410149557135.896118671 802129.98338905
#Sta/Elev= 30
9743.996741.40849759.026731.48839769.474728.16219800.819711.96419811.267708.5869
9832.163691.91159863.508680.57819873.956672.84149884.405668.33219894.853666.5809
9905.301667.24489926.198 661.6369947.094658.56049957.542653.37649978.439650.1892
10030.68  649.4610051.58650.505310072.47655.022410079.65658.145310103.82672.0945
10114.27683.853410135.16702.330610145.61700.672110166.51701.664510176.96705.9929
 10187.4715.541810197.85727.656110218.75755.172310239.65774.4086 10255.3786.0002
#Mann= 3 , 0 , 0
9743.996    0.04       09743.996    0.04       0 10255.3    0.04       0
#XS Ineff= 2 , 0
       0                               0
Bank Sta=9743.996,10255.3
Exp/Cntr=0.3,0.1